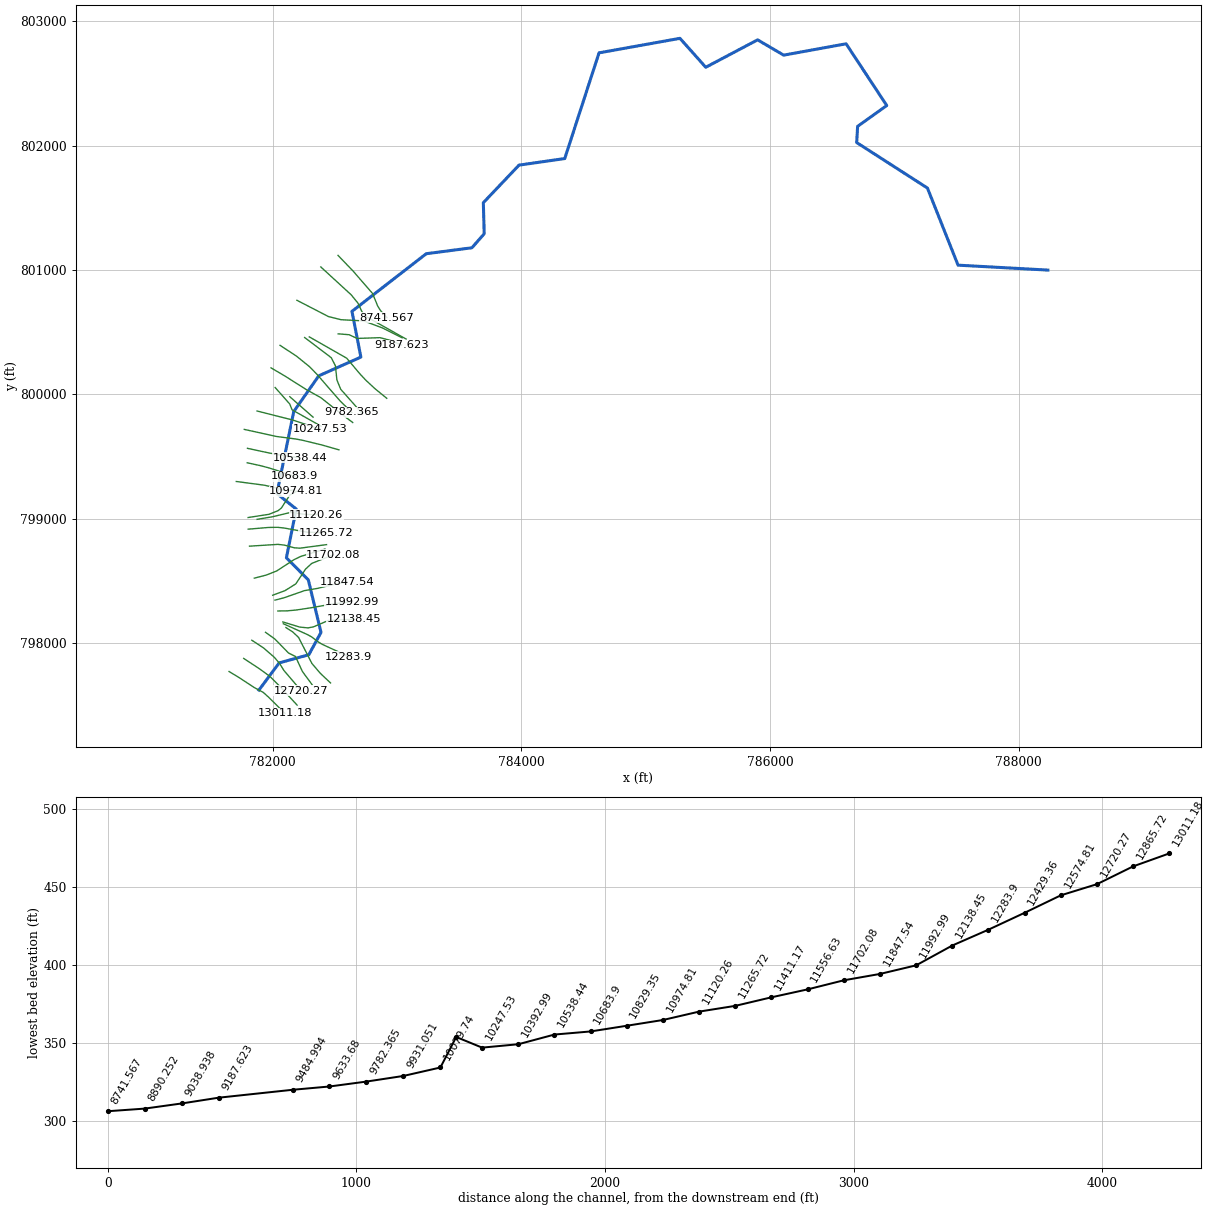
--- 17671_ras.prj (project) ---

Proj Title=17671
Current Plan=p01
Default Exp/Contr=0.3,0.1
English Units
Geom File=g01
Flow File=f01
Plan File=p01
Y Axis Title=Elevation
X Axis Title(PF)=Main Channel Distance
X Axis Title(XS)=Station
BEGIN DESCRIPTION:
RFD model 17671 exported to HEC-RAS
END DESCRIPTION:

--- 17671_ras.p01 (plan) ---

Plan Title=Plan 01
Program Version=4.10
Short Identifier=Plan 01
Geom File=g01
Flow File=f01
Subcritical Flow
Calc Critical at every XS
Secant Critical Depth

--- 17671_ras.f01 (steady flow) ---

Flow Title=Flow 01
Program Version=5.01
Number of Profiles= 6
Profile Names=10yr,25yr,50yr,100yr,100plus,500yr
River Rch & RM=17671,58,13011.18
  259.58  448.44  636.72  824.28 1203.45 2127.25
River Rch & RM=17671,58,12865.72
  264.54  456.95  648.74  839.76 1226.04 2160.96
River Rch & RM=17671,58,12720.27
  265.65  458.84  651.41  843.19 1231.06 2168.42
River Rch & RM=17671,58,12574.81
  267.58  462.15  656.08  849.21 1239.84 2181.46
River Rch & RM=17671,58,12429.36
  270.07   466.4  662.09  856.93 1251.12 2198.17
River Rch & RM=17671,58, 12283.9
  274.19  473.46  672.06  869.76 1269.85 2225.92
River Rch & RM=17671,58,12138.45
  275.56  475.81  675.38  874.03 1276.08 2235.14
River Rch & RM=17671,58,11992.99
  278.03  480.03  681.35   881.7 1287.29  2251.7
River Rch & RM=17671,58,11847.54
  278.57  480.97  682.67  883.41 1289.77 2255.38
River Rch & RM=17671,58,11702.08
  284.81  491.67  697.81   902.9 1318.23 2297.45
River Rch & RM=17671,58,11556.63
  291.25  502.73  713.47   923.1 1347.72 2341.03
River Rch & RM=17671,58,11411.17
  293.69   506.9  719.37  930.68  1358.8  2357.3
River Rch & RM=17671,58,11265.72
  295.84  510.59  724.59   937.4 1368.61 2371.71
River Rch & RM=17671,58,11120.26
  301.77  520.75  738.94  955.88 1395.58 2411.19
River Rch & RM=17671,58,10974.81
  311.93  538.29  763.86  988.08  1442.6 2480.55
River Rch & RM=17671,58,10829.35
  315.35  544.16  772.18  998.82 1458.28  2503.5
River Rch & RM=17671,58, 10683.9
  316.69  546.46  775.42 1002.99 1464.36  2512.3
River Rch & RM=17671,58,10538.44
  318.83  550.12   780.6 1009.65 1474.08 2526.37
River Rch & RM=17671,58,10392.99
  381.66  659.09  935.88 1210.94 1767.97 2955.05
River Rch & RM=17671,58,10247.53
  386.53  667.44  947.69 1226.13 1790.15 2986.36
River Rch & RM=17671,58,10079.74
  388.07  670.07  951.41 1230.92 1797.15 2996.22
River Rch & RM=17671,58,9931.051
  389.35  672.27  954.52 1234.92 1802.98 3004.42
River Rch & RM=17671,58,9782.365
  390.89   674.9  958.24 1239.71 1809.97 3014.26
River Rch & RM=17671,58, 9633.68
  392.17   677.1  961.34 1243.69 1815.79 3022.45
River Rch & RM=17671,58,9484.994
  396.26   684.1  971.25 1256.44  1834.4 3048.59
River Rch & RM=17671,58,9187.623
  405.18  699.38  992.84 1284.22 1874.96 3105.47
River Rch & RM=17671,58,9038.938
  460.94  795.65 1129.66 1461.06 2133.15 3468.15
River Rch & RM=17671,58,8890.252
  462.71  798.66  1133.9 1466.51  2141.1    3479
River Rch & RM=17671,58,8741.567
  464.46  801.66 1138.13 1471.94 2149.03 3489.83
River Rch & RM=17671,58,8592.881
  468.19  808.04 1147.15 1483.53 2165.95    3513
River Rch & RM=17671,58,8444.195
  472.43  815.29 1157.38 1496.67 2185.14 3539.19
River Rch & RM=17671,58, 8295.51
  473.43  816.99 1159.79 1499.76 2189.65 3545.34
River Rch & RM=17671,58,8146.824
  475.96   821.3 1165.85 1507.53 2200.99  3560.7
River Rch & RM=17671,58,7998.139
  477.22  823.44 1168.87  1511.4 2206.64 3568.37
River Rch & RM=17671,58,7849.453
  478.75  826.04 1172.52 1516.07 2213.46 3577.56
River Rch & RM=17671,58,7700.768
  488.11  841.96 1194.92 1544.76 2255.35 3634.06
River Rch & RM=17671,58,7552.082
  490.64  846.26 1200.98 1552.51 2266.66 3649.27
River Rch & RM=17671,58,7254.711
   497.4  857.78  1217.2  1573.3 2297.02 3690.22
River Rch & RM=17671,58,7106.025
  499.17  860.78 1221.42  1578.7 2304.91  3700.8
River Rch & RM=17671,58, 6957.34
  880.44 1521.33 2162.65 2797.41 4084.22  6055.1
River Rch & RM=17671,58,6808.654
  882.23 1524.37 2166.94 2802.91 4092.25 6065.06
River Rch & RM=17671,58,6659.969
  882.68 1525.13 2168.01 2804.29 4094.26 6067.55
River Rch & RM=17671,58,6511.283
  886.69 1531.97 2177.66 2816.65 4112.31 6089.94
River Rch & RM=17671,58,6362.598
  888.03 1534.25 2180.87 2820.77 4118.32 6097.39
River Rch & RM=17671,58,6213.912
  893.85 1544.16 2194.83 2838.65 4144.43 6129.66
River Rch & RM=17671,58,6065.227
  894.75 1545.69 2196.99  2841.4 4148.45 6134.62
River Rch & RM=17671,58,5916.541
  895.87  1547.6 2199.67 2844.84 4153.47 6140.81
River Rch & RM=17671,58,5767.855
   901.7 1557.52 2213.64 2862.72 4179.57 6172.99
River Rch & RM=17671,58, 5619.17
  903.27 1560.19  2217.4 2867.53  4186.6 6181.64
River Rch & RM=17671,58,5470.484
  904.17 1561.71 2219.55 2870.28 4190.61 6186.58
River Rch & RM=17671,58,5173.113
  904.84 1562.86 2221.15 2872.34 4193.62 6190.29
Boundary for River Rch & Prof#=17671,58,1
Up Type= 0
Dn Type= 2
Boundary for River Rch & Prof#=17671,58,2
Up Type= 0
Dn Type= 2
Boundary for River Rch & Prof#=17671,58,2
Up Type= 0
Dn Type= 2
Boundary for River Rch & Prof#=17671,58,2
Up Type= 0
Dn Type= 2
Boundary for River Rch & Prof#=17671,58,2
Up Type= 0
Dn Type= 2
Boundary for River Rch & Prof#=17671,58,2
Up Type= 0
Dn Type= 2

--- 17671_ras.g01 (geometry) ---

Geom Title=17671
Program Version=4.10

River Reach=17671,58
Reach XY= 30
781888.833525122797622.125119151782051.668870063797840.582266279
782290.148119033797906.325721813782388.134125441798086.050583843
782286.024876564798508.503062338 782109.90900785798686.074089897
782188.842773977799078.273032769782033.486290547799202.407465513
782168.937161296799862.158586463782370.613519489  800149.9486139
782708.807059678800300.225817768782637.140826794800668.187846698
783234.778171241801131.685252624783602.139282348801179.601919264
783700.750393482801292.101919261783693.764355629801542.110574088
783980.831104518801844.206302931784348.551294566801896.983889083
784624.378879132802747.183559944785275.094415873802863.947323351
785482.618402571 802631.23352873785899.695691467802851.800708142
786109.261249335802728.783449669786611.393604459802820.023465525
786938.345384418802323.521581865786704.066428362802156.201789764
786696.622069332802025.703582653787265.471840232801659.823964486
787511.794792176801039.617960416  788234.2688075801000.030343135

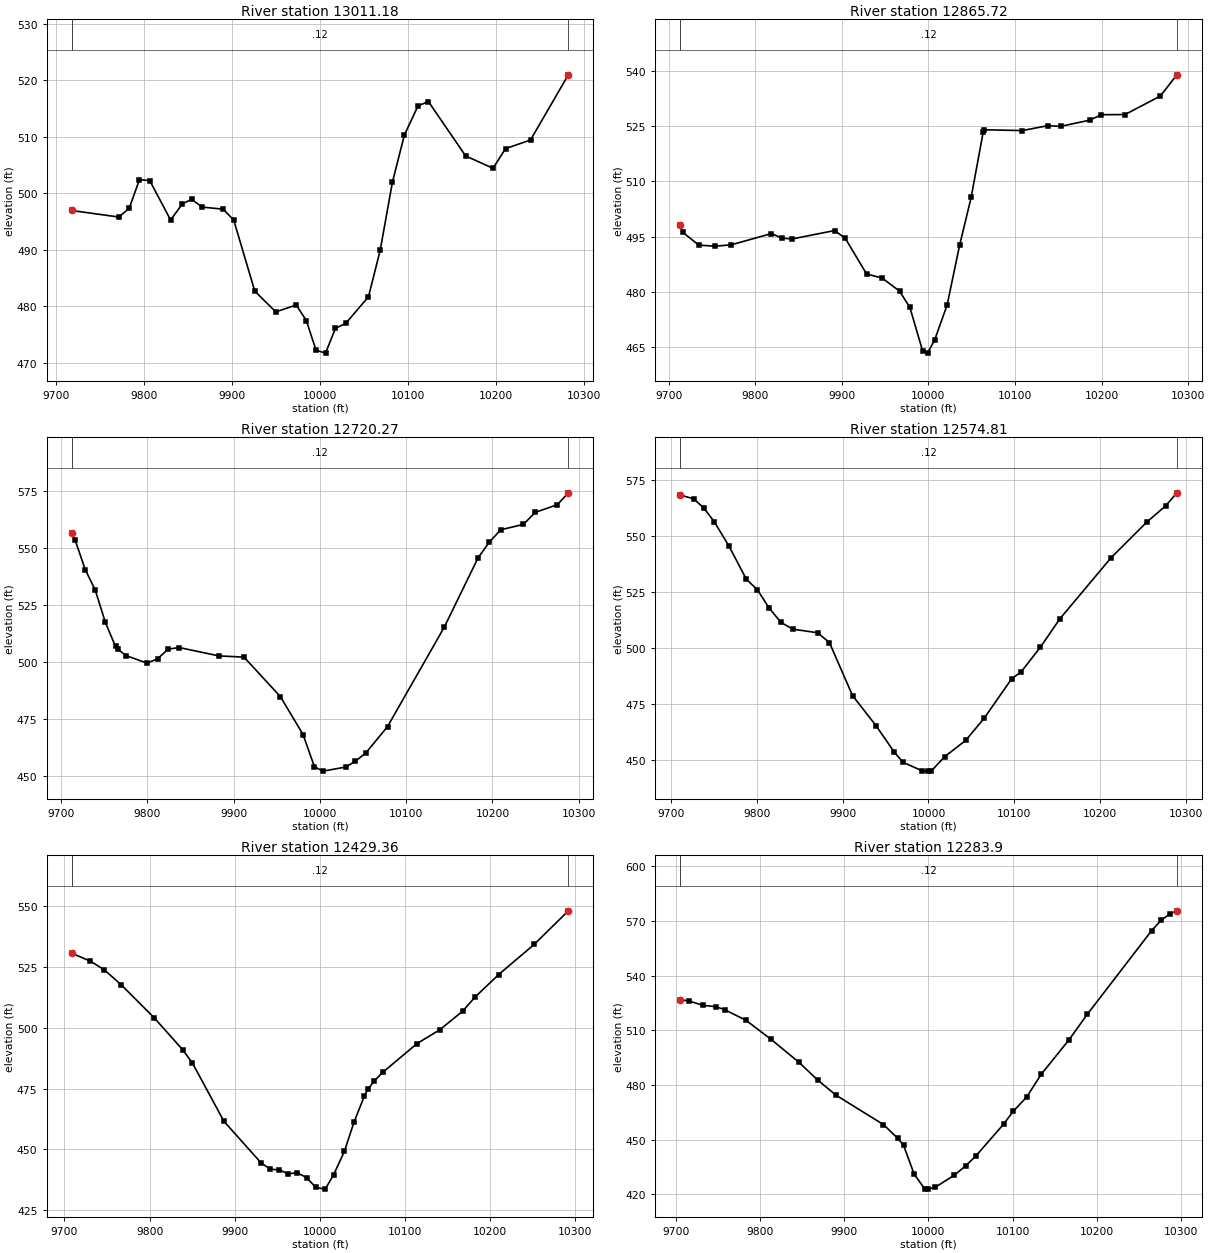
Type RM Length L Ch R = 1 ,13011.18,145.454800,145.454800,145.454800
XS GIS Cut Line= 6
781648.949091747797771.239438275781732.025338041  797720.8282996
781852.273807508797641.887537203781921.993549134 797604.60081255
 781965.51462304797565.979333692782097.925805969797434.711996805
#Sta/Elev= 30
9717.518496.96099771.384495.80189783.081497.34459794.778502.40459806.475502.2625
9830.213 495.2689843.535498.12929854.138498.9331  9866.1497.56329890.025497.1922
9901.987495.25859925.912 482.6879949.836479.01429973.123480.23249984.584477.4548
9995.524472.233610006.36471.709110017.59476.088810029.48476.999510055.19481.6842
10068.56 489.957 10082.4501.969410095.99510.303510111.59515.508810123.43516.2315
10165.67506.614810196.81504.432210211.01507.911510239.42509.441310282.44520.9778
#Mann= 3 , 0 , 0
9717.518    0.12       09717.518    0.12       010282.44    0.12       0
#XS Ineff= 2 , 0
       0                               0
Bank Sta=9717.518,10282.44
Exp/Cntr=0.3,0.1

Type RM Length L Ch R = 1 ,12865.72,145.454900,145.454900,145.454900
XS GIS Cut Line= 6
781766.548344507797876.584529732781887.000419764 797797.31776038
781949.289284616797752.826812683781984.065237095797725.266656754
782054.888357751797654.015061747782196.151568333797500.989967807
#Sta/Elev= 30
9713.077498.2677 9716.03496.23089734.668492.71839753.306492.42119771.943492.7808
9818.577495.84399830.674494.61029842.772494.39649891.698496.67489903.987494.5419
9928.564484.88269946.437483.79259966.641480.23629978.597475.78929993.245464.0241
    9999463.407510007.32  467.0710021.62476.493710035.93492.612910049.34505.6771
10063.32523.483610064.54524.009910108.33523.799510137.82  525.1210152.56524.9342
10186.22526.615510199.83528.094610227.05528.146310267.88533.162610286.94538.9225
#Mann= 3 , 0 , 0
9713.077    0.12       09713.077    0.12       010286.94    0.12       0
#XS Ineff= 2 , 0
       0                               0
Bank Sta=9713.077,10286.94
Exp/Cntr=0.3,0.1

Type RM Length L Ch R = 1 ,12720.27,145.454900,145.454900,145.454900
XS GIS Cut Line= 6
781831.473847851798023.184197457781926.343323068797960.920383246
782011.244409725797887.106673893782053.939628832797837.823969952
 782088.98935039797781.098748762782229.909001171797615.346999728
#Sta/Elev= 30
9712.149556.42319716.279553.59759727.993540.56499739.707531.4751 9751.42517.3083
9763.134 506.7639766.271505.45219775.134502.78159799.589499.47139811.817501.3006
9824.044505.57599836.797506.30069882.797502.63819912.074502.07529954.195484.7511
9980.509 468.0579993.665453.919110003.55452.010210029.73453.7907 10041.2456.3661
10053.26460.010810078.33471.571210143.96515.126310183.34545.749110196.46552.6659
10209.59558.031410235.84560.380410249.43565.648510275.21569.058110287.88574.2522
#Mann= 3 , 0 , 0
9712.149    0.12       09712.149    0.12       010287.88    0.12       0
#XS Ineff= 2 , 0
       0                               0
Bank Sta=9712.149,10287.88
Exp/Cntr=0.3,0.1

Type RM Length L Ch R = 1 ,12574.81,145.454900,145.454900,145.454900
XS GIS Cut Line= 6
781941.768823572798086.782324299782017.481580615798032.485953639
782126.670306628797920.443278522782182.783601559797892.181341279
782238.600357124797771.615242741782317.080949746797664.992520581
#Sta/Elev= 30
9710.499568.21049726.335566.45689738.303562.33979750.272 556.2999767.676545.2599
9787.795530.5237 9800.59525.89679814.158517.77069827.981511.30799841.804508.2737
9870.857506.65129884.565502.26569911.505478.60249938.923465.13069960.339453.2274
9970.313448.82389992.645444.9726    9999444.859510003.19444.9057 10018.9451.3215
10043.27 458.57210064.77468.421410097.03486.188410107.83489.108710130.43 500.244
10153.04512.863910212.81540.188310254.05555.975310276.56563.423210289.38569.1518
#Mann= 3 , 0 , 0
9710.499    0.12       09710.499    0.12       010289.38    0.12       0
#XS Ineff= 2 , 0
       0                               0
Bank Sta=9710.499,10289.38
Exp/Cntr=0.3,0.1

Type RM Length L Ch R = 1 ,12429.36,145.454800,145.454800,145.454800
XS GIS Cut Line= 6
782105.820592482798124.891026881782160.651223837 798089.98028185
782207.980972048798045.153751934782314.691588328797836.699186138
782382.044393757797757.233220958782464.863702991797679.460508139
#Sta/Elev= 30
9708.232530.66749730.335527.35419746.438523.88049766.455517.69739805.228504.1187
9838.767490.96889850.308485.46319887.205461.58359931.052444.40589941.672441.9151
9952.293441.52229962.913440.00139973.533440.35489984.353438.42739995.179434.3772
 10006.2433.676810016.17439.609710028.75449.1938 10040.2461.354810052.11471.8085
10056.08474.616210064.03478.188510073.91 481.70410114.19493.515710140.55499.0928
10167.64506.7908 10182.3512.616710209.88521.827310251.59534.2057 10291.8548.0325
#Mann= 3 , 0 , 0
9708.232    0.12       09708.232    0.12       0 10291.8    0.12       0
#XS Ineff= 2 , 0
       0                               0
Bank Sta=9708.232,10291.8
Exp/Cntr=0.3,0.1

Type RM Length L Ch R = 1 , 12283.9,145.454900,145.454900,145.454900
XS GIS Cut Line= 6
782085.587987484798155.457974694782282.095905737 798067.04300703
782315.571124041798048.177578413 782365.57257327798009.408597509
782398.939006463 797989.47371379782612.285996102797891.440273338
#Sta/Elev= 30
9704.561526.78139714.758526.15559731.744523.72859747.259522.97729757.737521.3001
 9782.84515.55959812.967505.00039846.063492.43759868.127482.76759890.191474.3808
9946.374458.31769963.721450.67549970.402446.89599983.017431.09899995.632422.9421
    9999422.867610008.37424.004410030.38430.366810044.41435.688110056.06440.8795
10089.62458.641810100.73465.530610116.72473.333810134.06485.825210166.93 504.637
10188.85518.744210265.56564.772710276.52570.281310287.48574.010310295.46575.5748
#Mann= 3 , 0 , 0
9704.561    0.12       09704.561    0.12       010295.46    0.12       0
#XS Ineff= 2 , 0
       0                               0
Bank Sta=9704.561,10295.46
Exp/Cntr=0.3,0.1

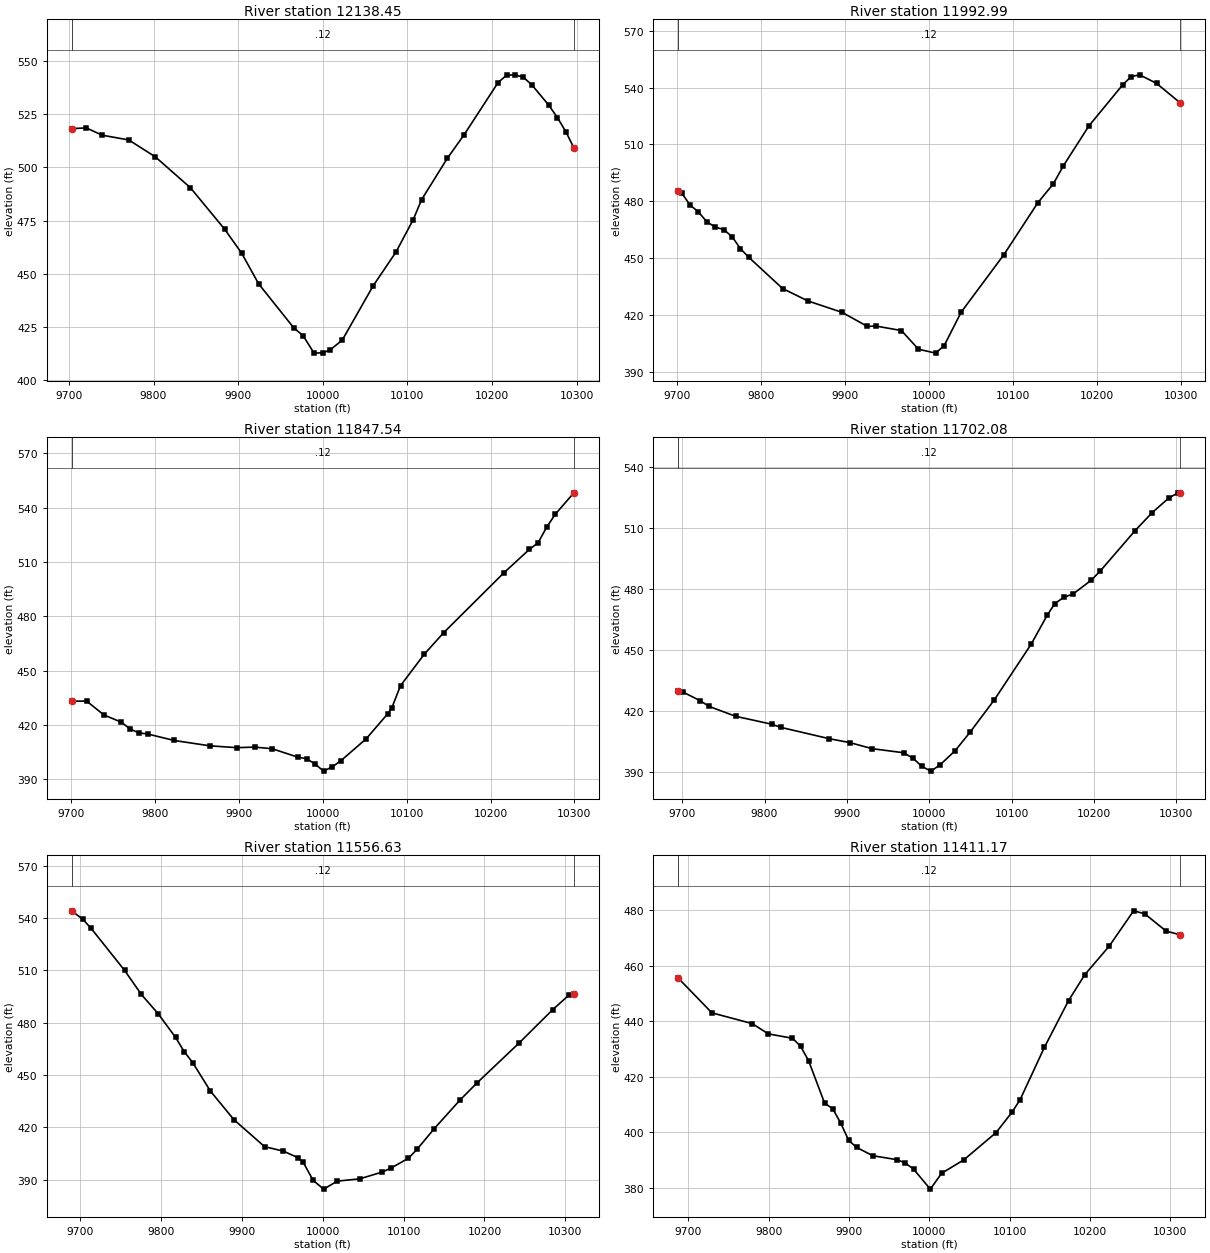
Type RM Length L Ch R = 1 ,12138.45,145.454900,145.454900,145.454900
XS GIS Cut Line= 6
782080.931175037798170.283462315 782216.56405815798129.014176479
 782283.05424129 798122.10318946 782328.37130124798130.829664693
782447.303814578798181.947984187782654.488874942798192.056989271
#Sta/Elev= 30
9703.402518.2267 9720.61518.5644  9739.2 515.1419770.723512.90089802.136504.9568
9843.589490.4418 9884.13 470.9079904.139 459.6819924.208445.27039965.791424.5484
9976.799 420.8979989.667412.7139 10000.1412.8635 10008.9414.263110023.07418.8805
10059.44444.295210086.44 460.199 10106.7475.311210116.81484.892610147.03504.1913
10167.09515.403710207.14539.883410217.14543.317110227.15543.504210237.15542.3371
10247.15538.728710267.16529.190410277.16523.446310287.16516.806610296.65509.2027
#Mann= 3 , 0 , 0
9703.402    0.12       09703.402    0.12       010296.65    0.12       0
#XS Ineff= 2 , 0
       0                               0
Bank Sta=9703.402,10296.65
Exp/Cntr=0.3,0.1

Type RM Length L Ch R = 1 ,11992.99,145.454900,145.454900,145.454900
XS GIS Cut Line= 6
782040.946677485798258.210711756 782113.50265217798259.264141147
782184.650651744798265.384574372782300.400767704798282.767792752
782494.002932651798316.890439494 782633.22406499798332.570468987
#Sta/Elev= 30
9701.138485.50779705.192484.40859715.193478.10669725.194474.41899735.195469.2281
9745.196466.42919755.197465.15049765.198461.42599775.204455.05789785.241450.4666
9825.389434.05939855.578427.50149896.026421.53139926.363414.09539936.475 414.287
9966.832 411.913 9987.15402.074310007.48400.012210017.64403.887810037.94421.5733
 10088.7451.804910129.31479.309410147.78489.284610159.76498.803310190.03519.7512
10230.36541.458210240.41545.744910250.45546.688110270.54542.205410298.88531.8682
#Mann= 3 , 0 , 0
9701.138    0.12       09701.138    0.12       010298.88    0.12       0
#XS Ineff= 2 , 0
       0                               0
Bank Sta=9701.138,10298.88
Exp/Cntr=0.3,0.1

Type RM Length L Ch R = 1 ,11847.54,145.454800,145.454800,145.454800
XS GIS Cut Line= 6
  782017.8239311798345.483835824782088.565348648798363.627335816
782254.887086052798421.798184977 782357.47062856798439.578826581
782502.862551801798473.997319621782596.899667188798492.465360887
#Sta/Elev= 30
 9700.69433.15789718.422433.14949738.994425.52779759.716 421.539 9770.04417.8644
9780.507415.61659791.053415.01459822.817411.41959865.539408.46479897.581  407.45
9918.789407.76749939.668406.85579970.434402.18459980.599401.37469990.764398.4335
10000.92394.497810011.05396.806810021.19400.1022 10051.6412.277810077.64426.2811
 10082.4429.530910092.67441.686910121.05459.074410144.05470.899410215.89503.9823
10246.46 516.97610256.65520.565610266.84  529.0710277.03 536.22410299.35548.1587
#Mann= 3 , 0 , 0
 9700.69    0.12       0 9700.69    0.12       010299.35    0.12       0
#XS Ineff= 2 , 0
       0                               0
Bank Sta=9700.69,10299.35
Exp/Cntr=0.3,0.1

Type RM Length L Ch R = 1 ,11702.08,145.454900,145.454900,145.454900
XS GIS Cut Line= 6
781999.290690045798385.064476682782098.067377967798421.547081178
782185.168763149798476.064606954782264.963004389 798596.29120542
782313.413303804798640.720169537 782488.21412336798710.739595426
#Sta/Elev= 30
 9695.26 429.8739701.233429.26029722.155425.01229732.617422.27769764.873417.3925
9808.616413.51529820.071411.92269878.657406.37199903.404404.46429930.831401.4564
9968.877399.46039980.289396.74659991.111392.708610002.01390.422310012.96393.4569
 10031.3400.432410049.53409.573510079.17425.611910123.71452.883910143.03467.0274
10152.37472.848210163.42475.944310174.41477.518710196.39484.265310207.25488.7288
10249.57508.6016 10270.3517.471910291.03524.8795 10301.4527.146810304.73527.3229
#Mann= 3 , 0 , 0
 9695.26    0.12       0 9695.26    0.12       010304.73    0.12       0
#XS Ineff= 2 , 0
       0                               0
Bank Sta=9695.26,10304.73
Exp/Cntr=0.3,0.1

Type RM Length L Ch R = 1 ,11556.63,145.454900,145.454900,145.454900
XS GIS Cut Line= 6
781851.560849983798522.203591235781947.509303523798547.014301869
782032.484959407798580.496319498782170.720338264798670.690308226
782225.138688186798697.077445304782420.567014065 798756.38698268
#Sta/Elev= 30
9689.446544.07949703.238539.1912  9713.5533.96659754.708510.00519775.555496.1547
9796.564484.97829817.842471.54969828.482463.46759839.121457.05479860.896440.8319
9889.958424.45329928.005408.9385 9951.24406.39719969.712402.53249975.497400.2247
9988.008389.628210001.04384.615410018.02389.222810045.56390.490510073.12394.3505
10084.06396.596910105.93402.290610116.63407.462210138.03419.353810169.88435.7481
10190.94445.555910243.03468.4251 10284.3487.402510304.49495.776610310.56496.2988
#Mann= 3 , 0 , 0
9689.446    0.12       09689.446    0.12       010310.56    0.12       0
#XS Ineff= 2 , 0
       0                               0
Bank Sta=9689.446,10310.56
Exp/Cntr=0.3,0.1

Type RM Length L Ch R = 1 ,11411.17,145.454900,145.454900,145.454900
XS GIS Cut Line= 6
781813.230663679798779.461512472782040.516000182798794.039168849
782093.536512933798788.330417537782171.986794549798766.654311977
782218.334990676798763.362820517782432.457937874798791.893443865
#Sta/Elev= 30
9687.333455.53119729.263443.01789779.456439.14059799.532435.44159829.648433.8637
9839.663 430.9989849.666425.80279869.671410.47979879.673408.51949889.676403.3332
9899.678397.0659 9909.68394.53169929.717391.55999959.932390.13169970.095388.9553
9980.489386.712210001.31379.533910015.45385.264210042.87390.034710083.19399.8856
 10103.2407.270910113.22411.795210143.33430.546610173.55447.4535 10193.8456.7919
10224.17467.048110254.54479.758310268.32478.689810295.03472.4634 10312.7471.0951
#Mann= 3 , 0 , 0
9687.333    0.12       09687.333    0.12       0 10312.7    0.12       0
#XS Ineff= 2 , 0
       0                               0
Bank Sta=9687.333,10312.7
Exp/Cntr=0.3,0.1

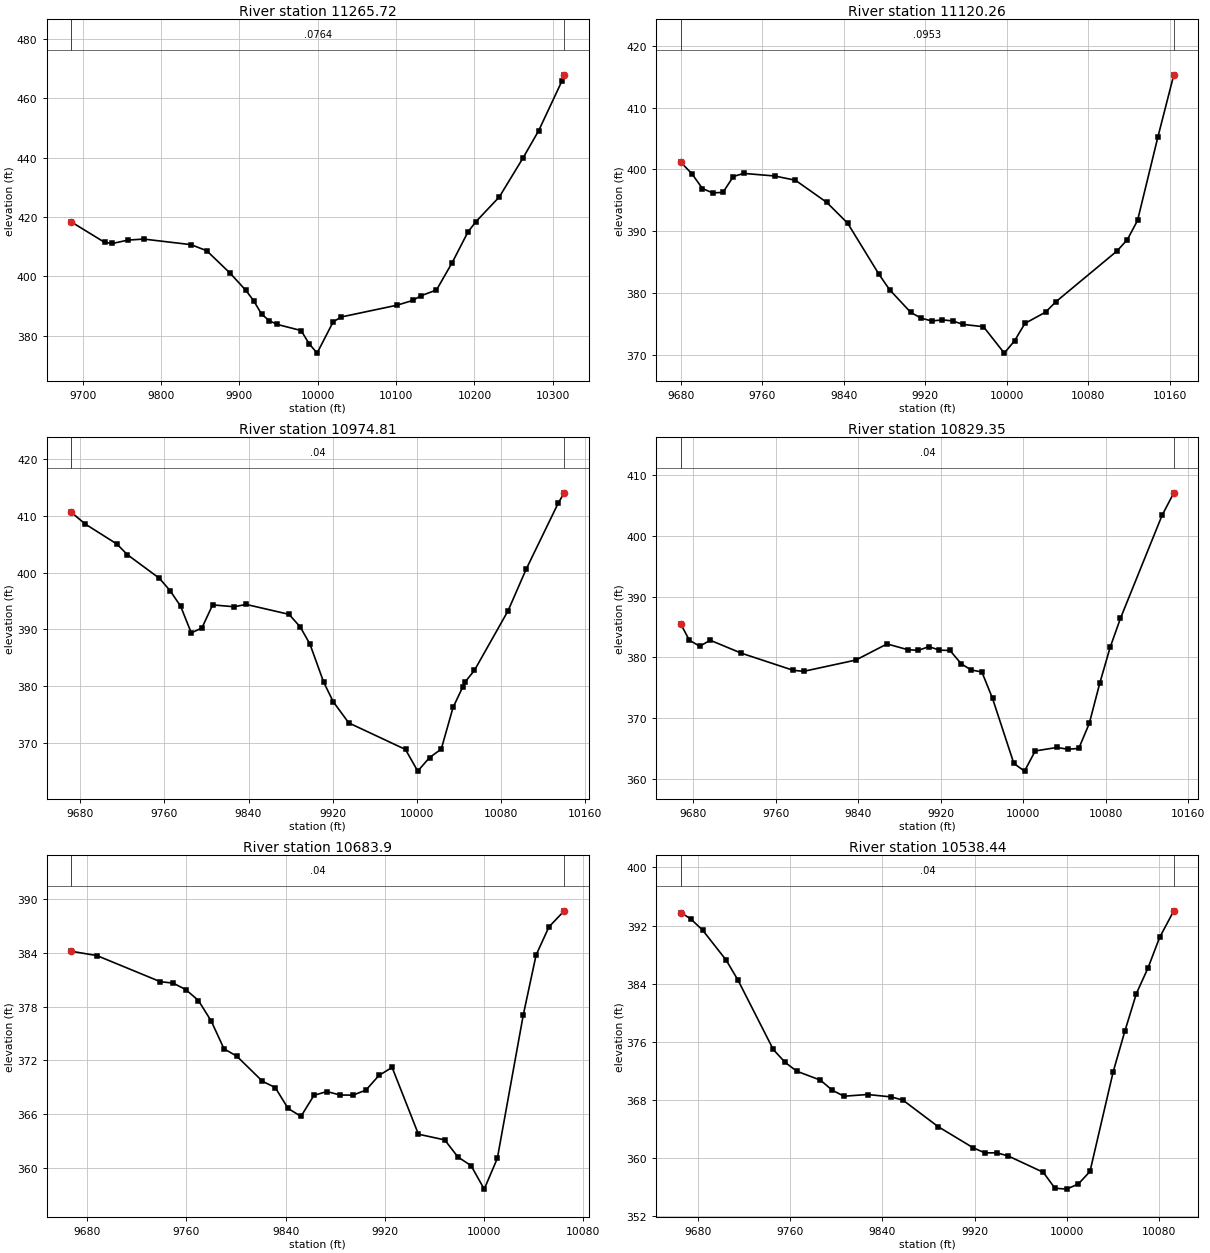
Type RM Length L Ch R = 1 ,11265.72,145.454800,145.454800,145.454800
XS GIS Cut Line= 6
781802.772256798 798916.34804294781964.753798195798929.909315209
782037.895835022798931.213465169782088.194613934798926.077106118
782276.346073271798892.129726629782427.770648749798887.522223634
#Sta/Elev= 30
9685.449 418.3329727.825411.4596 9737.86 411.057 9757.93412.2155    9778 412.548
 9838.21410.66789858.246408.6233 9888.25401.01539908.253395.22589918.255391.7308
9928.292387.21289938.344384.96189948.396383.7331 9978.67381.68899988.896377.2786
9999.123374.055410019.64  384.5910029.83386.246410100.93390.221410121.22391.8342
10131.32393.377610151.52395.360610171.66404.633410191.71414.945610201.74418.3847
10231.81426.796710261.81439.847210281.81449.045410311.81465.976110314.58467.9869
#Mann= 3 , 0 , 0
9685.449  0.0764       09685.449  0.0764       010314.58  0.0764       0
#XS Ineff= 2 , 0
       0                               0
Bank Sta=9685.449,10314.58
Exp/Cntr=0.3,0.1

Type RM Length L Ch R = 1 ,11120.26,145.454900,145.454900,145.454900
XS GIS Cut Line= 6
781874.078704804798995.370385923781997.654145303799015.823180481
782146.229722842799051.645878413782233.015070002799038.289512928
782283.566592247799034.162097033782350.610562804799033.195037354
#Sta/Elev= 30
9680.282401.16099691.313399.26419701.413396.92429711.513396.22279721.613396.3082
9731.713398.86279741.848399.36879772.357398.95279792.697398.2649 9823.38 394.704
 9843.92391.34859874.794383.07469885.174380.60359905.936376.93759916.316376.0008
9926.697 375.5569936.999375.73559947.132375.56439957.264375.00539977.337374.6314
9997.746370.368710007.87372.358510018.02375.1617 10038.3376.982910048.43378.6571
10108.59386.869110118.59388.689510128.59391.773910148.59405.2553 10164.2415.2761
#Mann= 3 , 0 , 0
9680.282  0.0953       09680.282  0.0953       0 10164.2  0.0953       0
#XS Ineff= 2 , 0
       0                               0
Bank Sta=9680.282,10164.2
Exp/Cntr=0.3,0.1

Type RM Length L Ch R = 1 ,10974.81,145.454900,145.454900,145.454900
XS GIS Cut Line= 6
781801.851534644799009.838770149781969.894148315799035.861093171
782044.154057849799065.571365723782069.819626392 799087.18973092
782137.615949641799190.933771941782190.140171915799220.181474896
#Sta/Elev= 30
 9671.35410.66029684.569408.6052 9714.73405.06799724.783403.18259755.114 399.031
9765.236 396.8669775.357394.10319785.478389.3901  9795.6390.25319805.797 394.333
9826.299394.0005 9837.65394.41569878.461392.66639889.113390.45679898.382387.4245
9911.529380.66629920.524377.25889935.331373.50669989.333368.817610000.95364.9974
10012.16367.379810023.36368.890210034.57376.233110043.59379.766210046.36380.7976
10054.93382.7857 10086.9393.291110104.06400.596310134.75412.327310140.34414.1059
#Mann= 3 , 0 , 0
 9671.35    0.04       0 9671.35    0.04       010140.34    0.04       0
#XS Ineff= 2 , 0
       0                               0
Bank Sta=9671.35,10140.34
Exp/Cntr=0.3,0.1

Type RM Length L Ch R = 1 ,10829.35,145.454900,145.454900,145.454900
XS GIS Cut Line= 6
781706.822718685799299.722075311781933.403374942799269.813906034
782041.128058051799243.879086895782085.920271521799228.720496613
782110.620875631799224.867372442 782176.24331726799231.872479606
#Sta/Elev= 30
9668.219385.43989676.454382.80919686.524381.83359696.594382.81899726.805380.6909
9777.156377.87279787.226377.7074 9837.72379.55739868.065382.21079888.294381.2576
9898.426381.16029908.647381.76889918.868381.18889929.088381.13679939.942378.9478
9949.641377.9286 9959.98377.60479970.319373.25549990.997362.567410001.32361.3098
10011.71364.625110032.83365.199310043.39364.905510053.94 365.042 10064.1369.1474
10074.22375.7261 10084.3381.629310094.31386.410910134.62403.320210146.05407.0401
#Mann= 3 , 0 , 0
9668.219    0.04       09668.219    0.04       010146.05    0.04       0
#XS Ineff= 2 , 0
       0                               0
Bank Sta=9668.219,10146.05
Exp/Cntr=0.3,0.1

Type RM Length L Ch R = 1 , 10683.9,145.454800,145.454800,145.454800
XS GIS Cut Line= 6
781794.778494706799450.417607219781898.043744927799427.782290807
781968.292321318799409.336825793782033.216534803799388.968384889
782137.271962458799352.008480255782176.964715007799341.675564518
#Sta/Elev= 30
9667.057384.16449687.759383.68229738.946380.77319749.184380.61829759.421379.8977
9769.658378.67939779.966376.39419790.305373.29549800.644372.47439821.322369.6813
9831.661368.9799    9842366.65759852.434  365.779862.915368.11419873.395368.5391
9883.876368.14799894.357 368.1389904.837368.69369915.343370.32619925.966371.2286
9947.211363.78429968.457 363.1479979.079361.24589989.702360.282310000.33357.6642
 10010.9361.089510031.86377.077110042.19 383.74410052.53386.871210064.89388.6705
#Mann= 3 , 0 , 0
9667.057    0.04       09667.057    0.04       010064.89    0.04       0
#XS Ineff= 2 , 0
       0                               0
Bank Sta=9667.057,10064.89
Exp/Cntr=0.3,0.1

Type RM Length L Ch R = 1 ,10538.44,145.454900,145.454900,145.454900
XS GIS Cut Line= 6
781796.670973077799566.438545026781962.738274185799530.722734904
782046.380853113799514.913756846 782124.22081904799502.608838085
782138.880575345799499.904614417782217.243101783799490.888679215
#Sta/Elev= 30
9665.205393.78719673.725392.90619683.954391.38469704.411 387.242 9714.64384.5015
9745.326374.91629755.554373.14789765.783371.9188 9786.24370.69179796.469 369.305
9806.697368.47579827.155368.71279847.549368.38139857.726367.94759888.257364.2947
9918.788361.3633 9928.92360.66489939.044360.68159949.168360.24189979.541357.9916
9989.665355.79949999.799355.672210009.97356.382510020.07 358.105 10040.2371.8397
10050.27377.417110060.33 382.629 10070.4386.149610080.46390.353610092.79394.0261
#Mann= 3 , 0 , 0
9665.205    0.04       09665.205    0.04       010092.79    0.04       0
#XS Ineff= 2 , 0
       0                               0
Bank Sta=9665.205,10092.79
Exp/Cntr=0.3,0.1

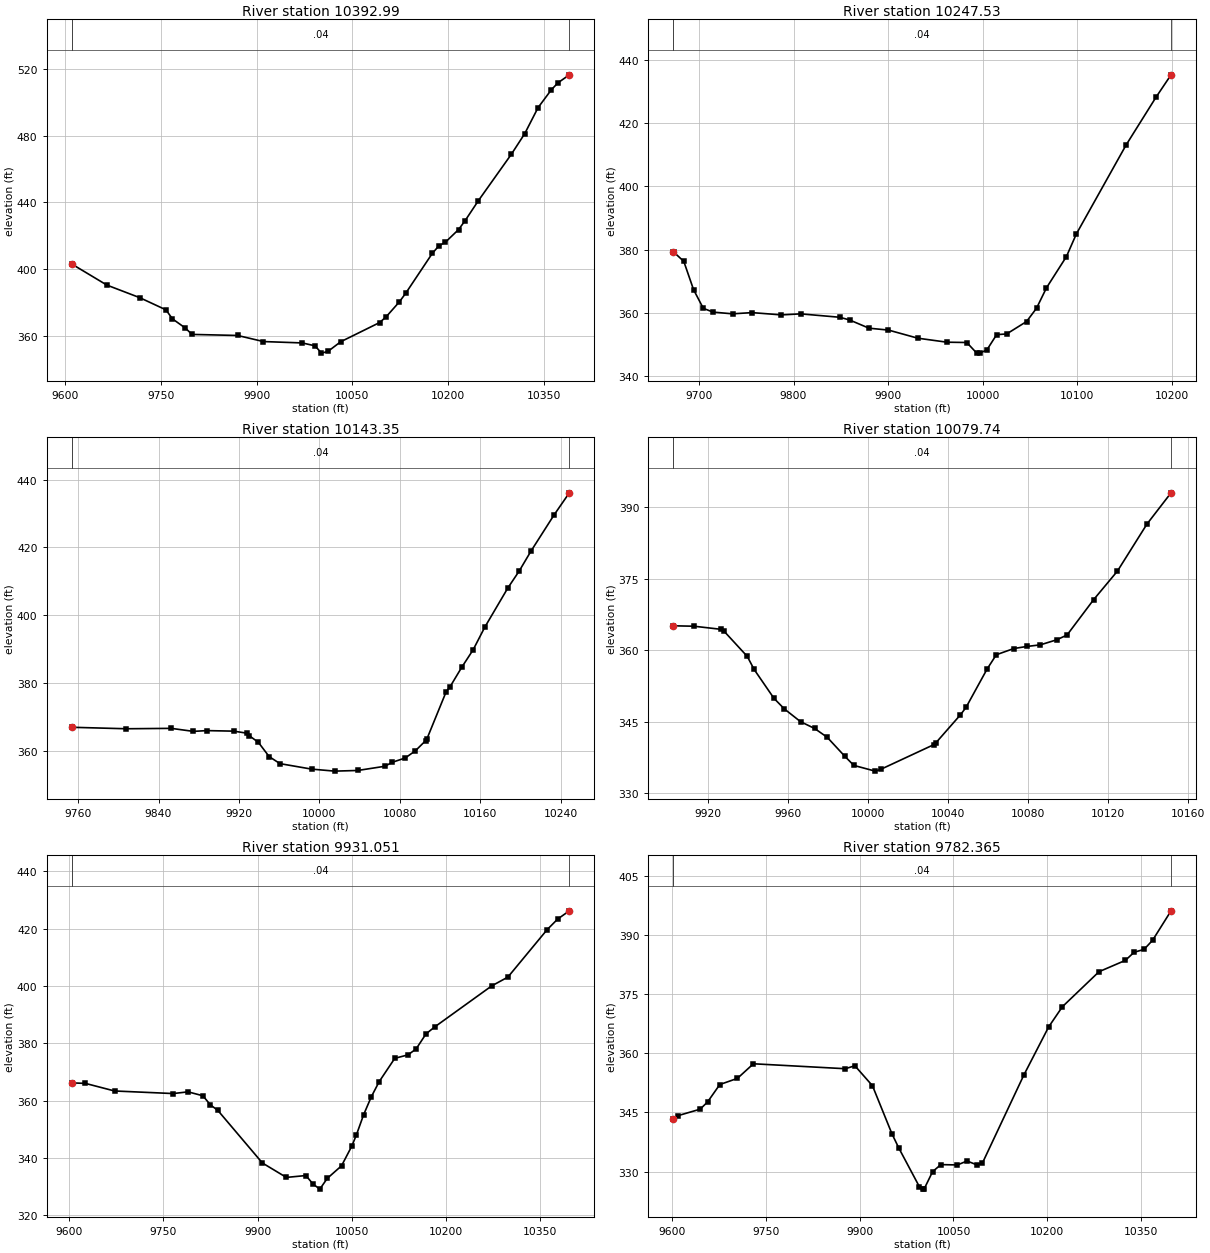
Type RM Length L Ch R = 1 ,10392.99,145.454900,145.454900,145.454900
XS GIS Cut Line= 6
 781771.10994913799718.608792332782030.771659203799661.554702623
782184.706431791799641.660597439782240.128768683799631.136849471
782396.538882817799593.086074275782532.093033054799554.196887716
#Sta/Elev= 30
9610.155402.9931 9665.52390.27249716.889382.7413 9757.97375.4342 9768.17370.0276
9788.568364.45059798.767360.68779870.161360.05719910.759356.40299971.538355.5785
9991.594 353.83610001.62349.462910011.65350.465810031.72356.290910092.85367.8344
10103.14 371.34810123.72380.259310134.02385.636410175.18409.286610185.47413.7995
10195.77416.025110216.35423.588110226.64 428.95310247.22440.838410299.22 468.867
10320.03481.155510340.84496.717610361.64507.423610372.05511.621310389.83516.4091
#Mann= 3 , 0 , 0
9610.155    0.04       09610.155    0.04       010389.83    0.04       0
#XS Ineff= 2 , 0
       09894.111                       0
Bank Sta=9610.155,10389.83
Exp/Cntr=0.3,0.1

Type RM Length L Ch R = 1 ,10247.53,104.188000,104.188000,104.188000
XS GIS Cut Line= 3
781874.225880235799866.606275022782160.398455828 799794.12914753
782380.071398914799720.904833153
#Sta/Elev= 30
 9672.75379.09779673.549379.13839683.864376.2898 9694.18 367.3739704.496 361.451
9714.812360.26049735.443359.71049756.075   360.19787.022 359.3769807.653359.6992
9848.916358.62489859.232357.78389879.863355.17399900.495354.57459931.442352.0155
9962.389350.74559983.349350.6486 9993.89 347.2929996.827347.321310004.43348.2257
10014.97353.142210025.51353.345410046.59357.275110057.14361.473310067.68367.9244
10088.76 377.792 10099.3384.9606   10152413.102510183.63428.190510199.51435.2491
#Mann= 3 , 0 , 0
 9672.75    0.04       0 9672.75    0.04       010199.51    0.04       0
#XS Ineff= 2 , 0
       09925.545                       0
Bank Sta=9672.75,10199.51
Exp/Cntr=0.3,0.1

Type RM Length L Ch R = 1 ,10143.35,63.609800,63.609800,63.609800
XS GIS Cut Line= 4
 782019.18013525800055.644556001782136.488475591799923.392478004
782155.168147653799876.319704488782388.290454596799744.814813361
#Sta/Elev= 30
9753.471367.0235  9807.8366.5863 9852.66366.70159874.636365.81379888.003366.0399
9914.737365.8834 9928.01365.27659930.253364.53669939.282362.5802 9950.04358.3759
9960.799356.30959992.185354.699510015.15354.104710038.11354.2982   10065355.5324
10072.55356.718410085.35 357.97610095.52360.1183 10105.7363.0945   10107363.6576
10126.06377.492810129.96378.978110141.44384.643710152.92389.8645 10164.4396.4698
10187.37 408.04110198.85413.124310210.33418.877810233.29429.536310248.55436.0857
#Mann= 3 , 0 , 0
9753.471    0.04       09753.471    0.04       010248.55    0.04       0
#XS Ineff= 2 , 0
       09979.523        10038.59       0
Bank Sta=9753.471,10248.55
Exp/Cntr=0.3,0.1

Type RM Length L Ch R = 1 ,10079.74,148.685600,148.685600,148.685600
XS GIS Cut Line= 2
 782137.23566246 799981.67305477782324.032382846799817.291940853
#Sta/Elev= 30
9902.596365.12339912.939365.03469926.259364.39279927.834364.0501 9939.58358.6867
9942.972355.97069952.901349.88549958.109347.64989966.221344.96089973.246343.5354
9979.542341.68029988.383337.66849992.863335.767810003.52334.567310006.18334.9185
10032.82340.132510033.79 340.48410046.15346.411110048.93347.963810059.47356.0365
10064.07359.034810072.79360.339710079.21360.772710086.11361.120110094.34362.1909
10099.43363.186410112.75370.636610124.62376.626510139.39386.522510151.42393.0812
#Mann= 3 , 0 , 0
9902.596    0.04       09902.596    0.04       010151.42    0.04       0
#XS Ineff= 2 , 0
       0                               0
Bank Sta=9902.596,10151.42
Exp/Cntr=0.3,0.1

Type RM Length L Ch R = 1 ,9931.051,148.685500,148.685500,148.685500
XS GIS Cut Line= 6
781986.016381685800213.673248692782097.231192183800148.380107806
782268.420373332800039.968254568782387.783325239799973.354239849
782564.359556167799832.897323063782643.373701294799773.932371344
#Sta/Elev= 30
 9603.69366.21079625.703366.03029672.087363.38649765.524362.48479789.197363.0815
 9812.87361.71229824.707358.55999836.543356.62749907.563338.27519945.749333.2441
9976.847333.8976 9988.21330.9262    9999329.159110010.87332.905210033.59337.2948
10049.72344.067210057.04347.926110068.76355.110710081.01  361.3610093.47366.6238
10118.38374.7759 10139.4375.977210152.32378.037910168.11 383.29810182.21  385.76
10272.68400.0247 10298.5403.101210360.89419.621210377.79423.3418 10396.3426.2046
#Mann= 3 , 0 , 0
 9603.69    0.04       0 9603.69    0.04       0 10396.3    0.04       0
#XS Ineff= 2 , 0
       0                               0
Bank Sta=9603.69,10396.3
Exp/Cntr=0.3,0.1

Type RM Length L Ch R = 1 ,9782.365,148.685600,148.685600,148.685600
XS GIS Cut Line= 6
782058.756420239800394.669862311782188.920527489800309.452984254
782294.154798517800224.415704321782352.543670583800165.027754006
782543.662781044799945.539765327782636.813711186 799855.09442898
#Sta/Elev= 30
9602.427343.22219609.811344.16159645.287345.80459657.113347.62299676.747352.0521
 9704.85353.61529730.459357.31369877.243356.06129892.506356.81189920.626351.7445
9951.658339.59859962.697335.96269995.561326.1649   10001325.551310003.36325.6458
10016.61329.965710029.86331.763410056.37331.680610071.68332.680910086.91331.7329
10096.13332.1116 10162.4354.447310202.16366.677210224.04371.7756 10282.5380.6424
10324.56383.510710338.58385.568810354.48386.299110368.11388.6106 10397.6  396.07
#Mann= 3 , 0 , 0
9602.427    0.04       09602.427    0.04       0 10397.6    0.04       0
#XS Ineff= 2 , 0
       0                10074.63       0
Bank Sta=9602.427,10397.6
Exp/Cntr=0.3,0.1

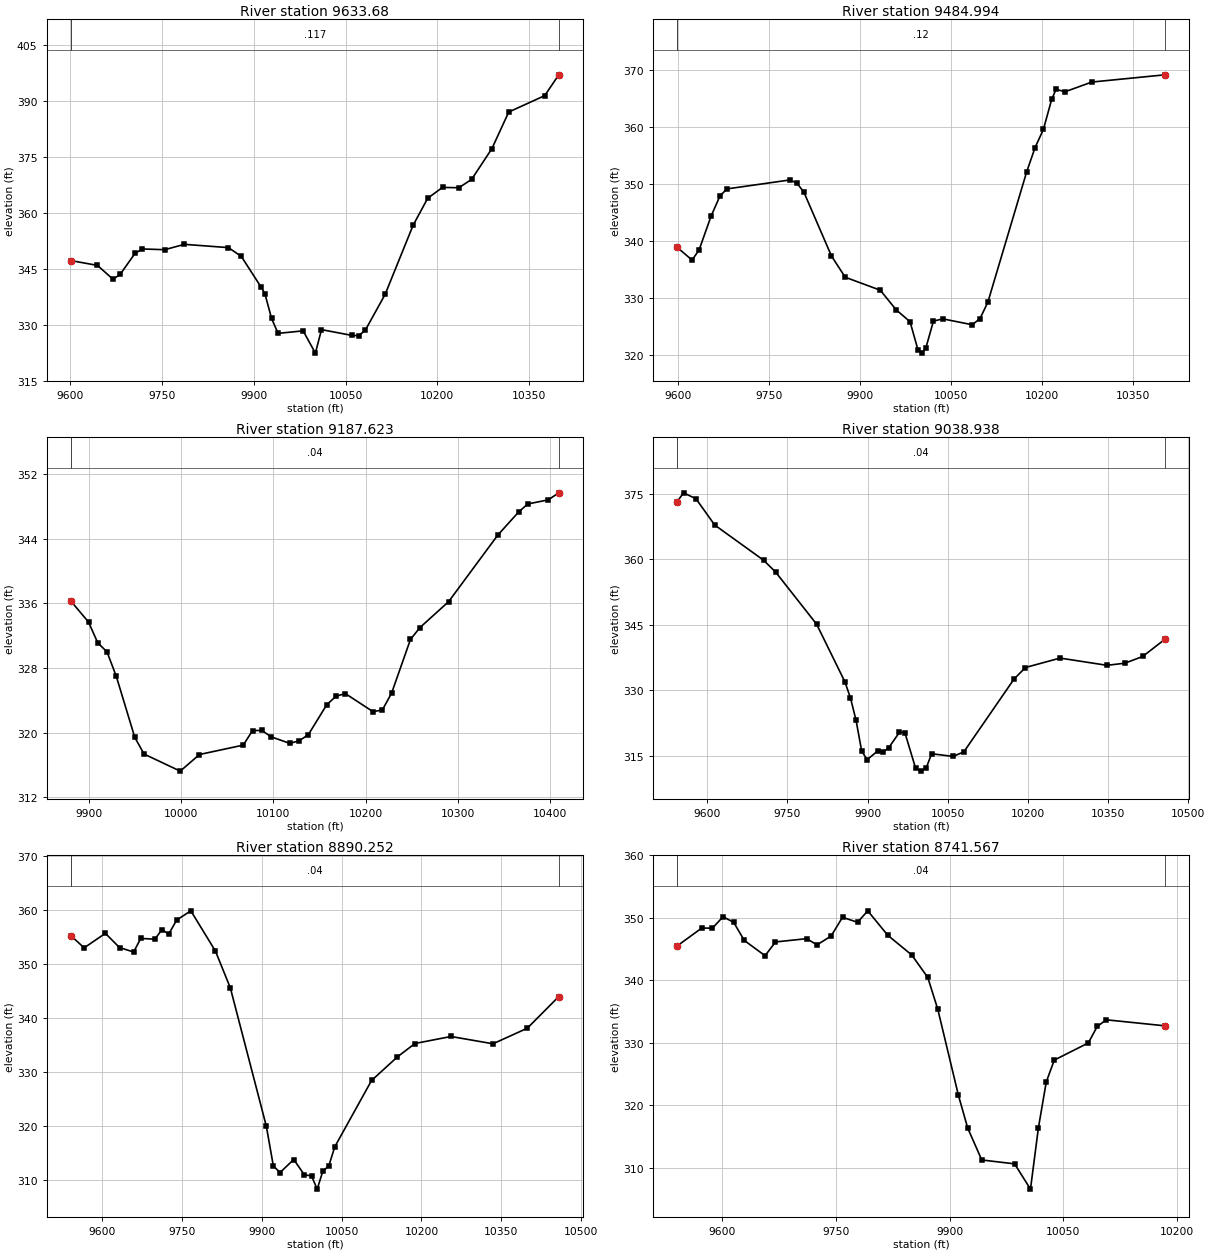
Type RM Length L Ch R = 1 , 9633.68,148.685500,148.685500,148.685500
XS GIS Cut Line= 6
782256.750075017800457.802752649782470.959666977800295.002829638
782503.993812142800230.075350482782516.139525984800115.894269517
782546.557741173800041.584003341 782716.84057708799849.606289735
#Sta/Elev= 30
9601.506347.17479644.641345.89439670.129342.1809 9681.91 343.5219705.917349.0897
9718.087350.29789754.597350.09829786.677351.53499858.714350.65529879.706348.3081
9912.224340.04419918.354338.28799929.092331.72259939.829327.6937 9980.76328.3633
10000.77322.398710010.77328.689410061.23327.122510071.72327.112310082.22328.4926
10114.74  338.1310160.54356.666610184.35363.878410208.58366.788910235.14366.6887
10256.06368.922310289.23377.170310316.78386.971110375.57 391.36510398.52396.9332
#Mann= 3 , 0 , 0
9601.506   0.117       09601.506   0.117       010398.52   0.117       0
#XS Ineff= 2 , 0
       0                               0
Bank Sta=9601.506,10398.52
Exp/Cntr=0.3,0.1

Type RM Length L Ch R = 1 ,9484.994,297.371100,297.371100,297.371100
XS GIS Cut Line= 6
782293.642666555800463.065634798782595.093145259800291.209358229
782700.070675806800166.346107317782747.892139422800115.205731209
782820.537549113800047.475534292 782916.83323497799968.868748616
#Sta/Elev= 30
9597.982338.84859622.631336.61039634.173338.37419654.193344.37479668.797347.8974
9680.339349.09669784.213350.66799795.754350.08179807.196348.47029852.485337.3183
 9875.13 333.5979932.969331.31969959.188327.87479982.002325.79679994.959320.8911
   10001320.283410007.82  321.1110020.61325.9049 10036.1326.292810084.55325.2624
10097.34326.337410110.25329.208310174.19 352.05910188.14356.352810201.81359.5203
10215.48364.785610222.72366.567710237.38366.132310281.66367.837910402.05369.1062
#Mann= 3 , 0 , 0
9597.982    0.12       09597.982    0.12       010402.05    0.12       0
#XS Ineff= 2 , 0
       0                               0
Bank Sta=9597.982,10402.05
Exp/Cntr=0.3,0.1

Type RM Length L Ch R = 1 ,9187.623,148.685600,148.685600,148.685600
XS GIS Cut Line= 6
782526.110392469800487.154061427782614.021414654 800480.30248598
 782679.10092417800450.327167388782862.804398893800456.576622976
782948.719202119800434.133132998 783035.35242327800396.457327913
#Sta/Elev= 30
9880.643336.26159899.567333.69529909.585331.11479919.603329.99519929.621 326.989
9949.677319.41139959.762317.3325    9999315.215610019.83317.274410067.29318.4397
10077.38320.245310087.46320.256510097.54 319.46610117.71318.658410127.79318.9699
10137.82319.725610157.87323.459310167.88 324.49710177.88324.831610207.98322.5844
10218.04322.791210228.13324.891210248.55  331.5410258.77333.002810289.96336.2287
10343.13344.459110365.78347.330910375.63348.324210397.81348.8321 10409.3349.7072
#Mann= 3 , 0 , 0
9880.643    0.04       09880.643    0.04       0 10409.3    0.04       0
#XS Ineff= 2 , 0
       0                10074.49       0
Bank Sta=9880.643,10409.3
Exp/Cntr=0.3,0.1

Type RM Length L Ch R = 1 ,9038.938,148.685500,148.685500,148.685500
XS GIS Cut Line= 6
782194.542515408800757.139838833782447.515133528800626.406386114
782549.308387855800600.862568333782730.429947171800591.553002972
782883.891823286800534.004272465783040.862240181800455.298210607
#Sta/Elev= 30
9543.789373.14569555.953375.16059579.216373.78549614.111367.79759705.573359.7466
9727.973357.05699804.741345.12649857.711331.9417 9868.16328.2346 9878.61323.1219
 9889.06316.13279899.226314.13299919.559316.18959929.725 315.9289939.805316.8973
9959.835320.4145 9969.85320.35159989.877312.21569999.889311.521810009.92312.2855
10019.96315.503310060.05314.878910080.19315.922910174.09332.5676 10195.4335.2119
10260.17337.370310348.12335.717410381.34336.199310414.85337.741710456.23341.6658
#Mann= 3 , 0 , 0
9543.789    0.04       09543.789    0.04       010456.23    0.04       0
#XS Ineff= 2 , 0
       09955.664                       0
Bank Sta=9543.789,10456.23
Exp/Cntr=0.3,0.1

Type RM Length L Ch R = 1 ,8890.252,148.685600,148.685600,148.685600
XS GIS Cut Line= 6
782386.509330821801025.512568929782631.789800957800800.301335008
 782685.01041392800734.414653033782717.877546335800664.462099096
782750.292052875800626.622403831783072.317454175 800445.61756284
#Sta/Elev= 30
9542.324355.25489566.874353.02029606.707355.71019633.261353.07689659.816352.2428
9673.093354.76749699.648 354.6269712.926356.41859725.519355.56179740.575358.1842
 9767.12359.89069813.242  352.439841.257345.58159908.869319.87779921.965312.5336
9934.478311.30699960.237313.72999979.834310.92959993.668310.659710004.25308.2313
10014.86311.569610025.99312.529710037.21316.079410106.28328.3961 10154.8332.7824
10187.75335.262710255.34336.562810334.19335.210110398.53338.097710457.62343.9715
#Mann= 3 , 0 , 0
9542.324    0.04       09542.324    0.04       010457.62    0.04       0
#XS Ineff= 2 , 0
       0                               0
Bank Sta=9542.324,10457.62
Exp/Cntr=0.3,0.1

Type RM Length L Ch R = 1 ,8741.567,148.685500,148.685500,148.685500
XS GIS Cut Line= 6
782525.143798615801118.154579856782648.405630217800989.721567925
782802.921624489800811.723055097782844.658586688800709.772218841
782865.488340811800676.376600523782918.720614802800618.268508007
#Sta/Elev= 30
9540.872345.5007 9573.36348.37679587.391348.35319601.422350.18729615.453349.2867
 9629.43346.38779656.841343.94259670.546346.14679711.663346.67559725.217345.6802
9743.866 347.0939758.911350.09739778.752349.29669792.136351.13369818.625347.2095
9850.213344.05499871.296340.45739884.463335.37169911.698321.56519923.966316.3175
 9942.44311.22019985.727310.598110006.67306.549510017.06316.330510027.46323.7126
10038.02 327.221 10082.9329.966310094.69332.617910106.62333.675810183.76332.7109
#Mann= 3 , 0 , 0
9540.872    0.04       09540.872    0.04       010183.76    0.04       0
#XS Ineff= 2 , 0
       0                               0
Bank Sta=9540.872,10183.76
Exp/Cntr=0.3,0.1