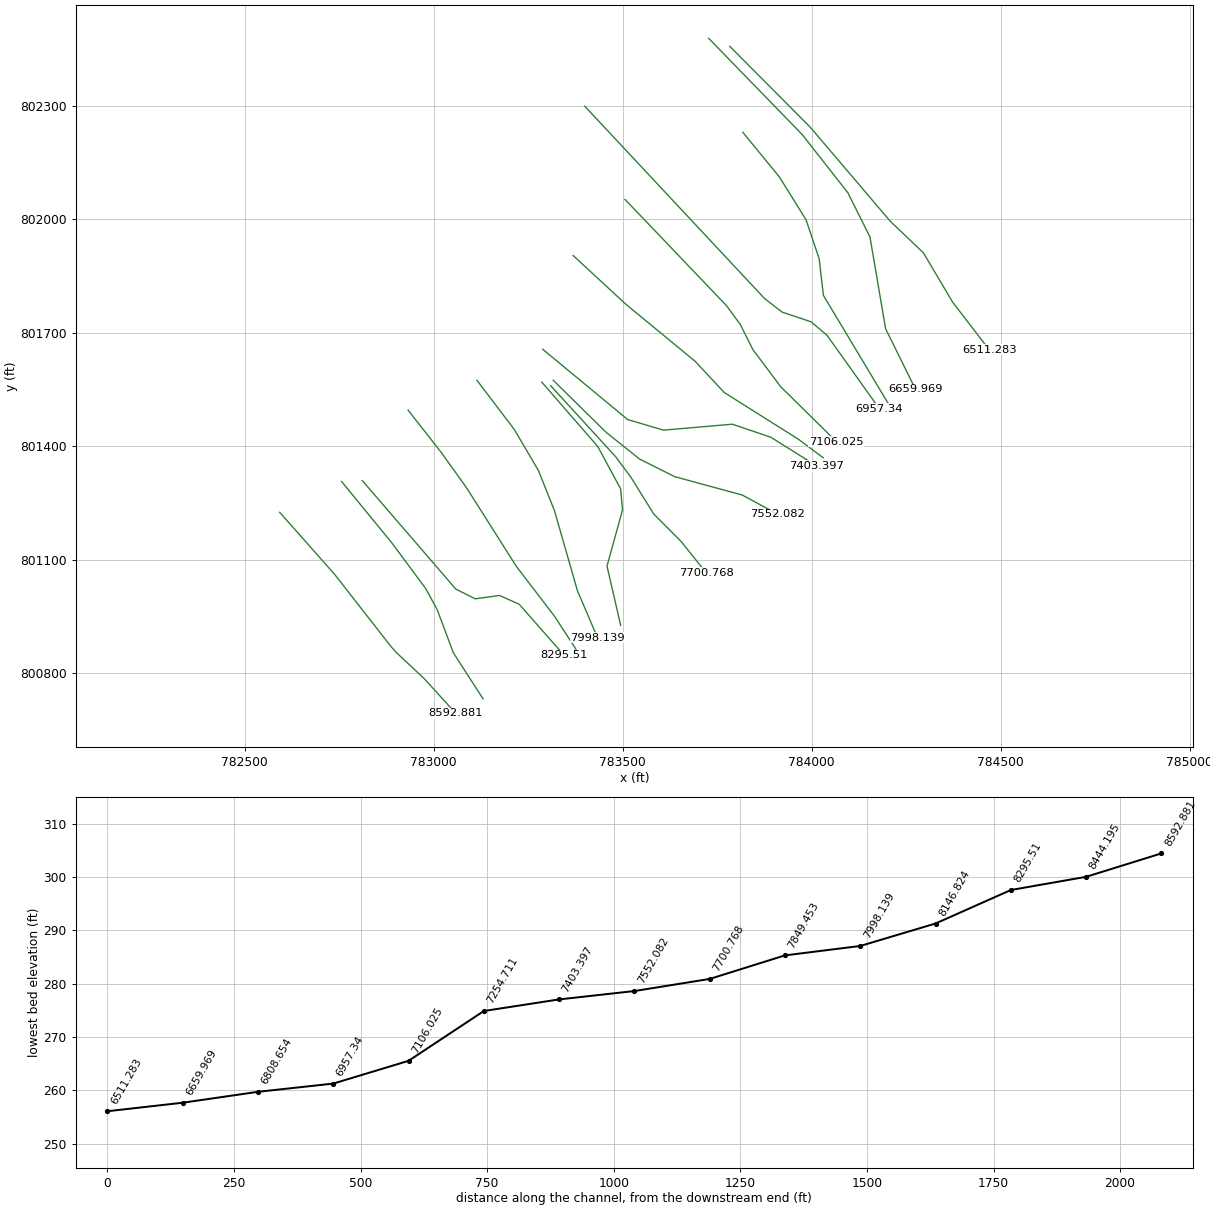
HEC-RAS study 17671_ras.prj: 17671

--- 17671_ras.g01 (geometry) --- (continued)

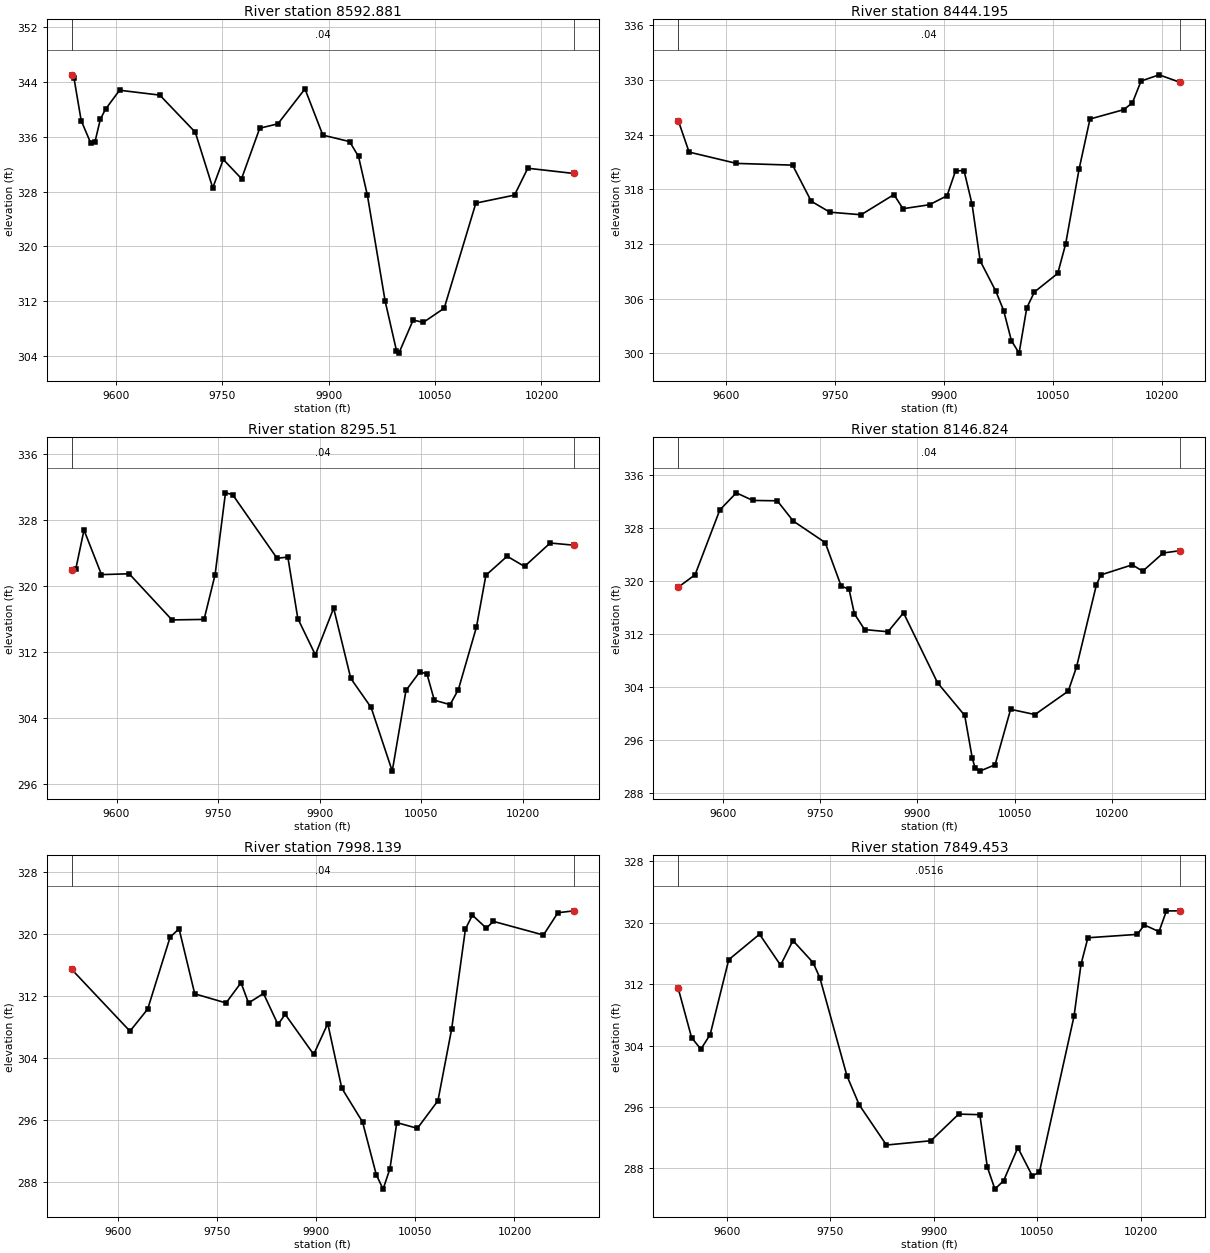
Type RM Length L Ch R = 1 ,8592.881,148.685600,148.685600,148.685600
XS GIS Cut Line= 6
 782592.96078824801224.809514665782737.370259038801061.834522782
782887.204991419800870.041115468782901.007417717 800854.34448176
782975.591473552800784.639744963783058.610987259800693.019088713
#Sta/Elev= 30
9537.818345.05869540.847344.64139551.084 338.3769564.608335.06889570.554335.2716
9578.132338.58219585.408340.0337 9605.18342.80589661.903 342.0969711.966336.6677
9736.554328.5417 9751.43332.69149777.163329.87719802.787337.25779828.412337.8981
9866.586343.00279891.741336.25199929.473335.30429942.051333.12989954.628327.4354
9979.535312.02779995.578304.7571    9999304.396310019.03 309.21910033.59308.8997
10062.88310.959710107.49326.313110161.99327.484610180.68331.409810245.63330.6446
#Mann= 3 , 0 , 0
9537.818    0.04       09537.818    0.04       010245.63    0.04       0
#XS Ineff= 2 , 0
       0                               0
Bank Sta=9537.818,10245.63
Exp/Cntr=0.3,0.1

Type RM Length L Ch R = 1 ,8444.195,148.685500,148.685500,148.685500
XS GIS Cut Line= 6
782756.658398668801306.451926782782890.414339926 801142.99388973
782979.508937054801022.706231178783009.638536083800967.304792571
 783052.13129298800853.560526268783130.775846509800731.580463886
#Sta/Elev= 30
9534.419325.53529549.358322.07289614.584320.83339691.786320.64169717.427316.6803
9743.068315.47949786.115 315.1979831.233317.40929843.721315.86029880.349316.2993
9904.356 317.2879916.031320.00839927.684 320.0529938.806 316.3439949.928310.1365
9971.592306.78839982.243304.68679992.894301.3792 10003.5300.010310014.06304.9847
10024.62306.722510056.71308.764410067.55311.9854   10086320.181910101.05325.7029
10147.42 326.72910159.36327.469410171.34329.871610196.22330.553310225.36329.7204
#Mann= 3 , 0 , 0
9534.419    0.04       09534.419    0.04       010225.36    0.04       0
#XS Ineff= 2 , 0
       0                               0
Bank Sta=9534.419,10225.36
Exp/Cntr=0.3,0.1

Type RM Length L Ch R = 1 , 8295.51,148.685600,148.685600,148.685600
XS GIS Cut Line= 6
 782811.32086825801308.992187863783058.816832995801021.840927136
783110.257456811800996.050718151783174.405565228801004.990713201
783226.633683262800981.623627248783345.609909718 800846.37729156
#Sta/Elev= 30
9533.887321.94799539.702321.97799551.954326.7515 9577.78321.34929618.733321.4487
9681.958315.85869729.377315.91949745.645321.33929760.989331.25929771.471331.0484
9837.151323.33479853.165323.46859867.909316.0202 9893.82311.62139920.817317.2863
9946.121308.77279976.182305.2496 10007.4297.5355 10027.7307.315610048.07309.5623
10058.66309.324710069.57306.130910092.84305.594210105.05307.407510131.81314.9878
10145.74321.265710177.14323.573810202.85322.338910240.77325.179710275.72324.9118
#Mann= 3 , 0 , 0
9533.887    0.04       09533.887    0.04       010275.72    0.04       0
#XS Ineff= 2 , 0
       0                               0
Bank Sta=9533.887,10275.72
Exp/Cntr=0.3,0.1

Type RM Length L Ch R = 1 ,8146.824,148.685500,148.685500,148.685500
XS GIS Cut Line= 6
782932.488022574801495.427495875783019.946917464801383.749236289
783086.925903065 801290.37086253783218.638629672801082.485338642
783320.442713969800949.251322313783376.599602052800862.936669143
#Sta/Elev= 30
9531.575319.08549557.521320.97049595.626330.76829621.029333.36539646.432332.2136
9684.191332.15799708.804329.0931 9758.03325.83639782.643319.24949794.779318.7823
 9802.98315.06439818.755312.67639854.719312.34449878.696315.20789931.121304.6293
9972.988299.68249984.668293.20499989.175291.68779996.349291.260710019.79292.2234
10043.72300.615210081.26299.8187 10132.5303.365810145.31307.031610175.97319.4588
10182.73 320.94610231.14322.474210247.24321.508510278.86 324.26310305.19324.6196
#Mann= 3 , 0 , 0
9531.575    0.04       09531.575    0.04       010305.19    0.04       0
#XS Ineff= 2 , 0
       0                               0
Bank Sta=9531.575,10305.19
Exp/Cntr=0.3,0.1

Type RM Length L Ch R = 1 ,7998.139,148.685600,148.685600,148.685600
XS GIS Cut Line= 6
783114.772574723801574.122334566783213.562208028801444.172495257
783277.507616129801335.284351733 783319.77880232801229.473635771
783380.608086806801017.442652953783433.670286541800893.432454749
#Sta/Elev= 30
9530.601 315.422 9618.62307.4517 9645.37310.29919679.336319.59869692.854320.6735
9716.555312.27699763.867311.09649786.562313.70729797.895311.08989820.548312.3199
9842.411308.31759853.343309.62579896.472304.44839917.738308.43679938.928300.0896
9970.317295.72469991.125288.908310001.41  287.0510011.78289.700310022.14295.6415
10053.25294.904410084.35 298.46510105.09307.735110125.94320.645210136.45322.4329
10157.49320.757410168.18321.632510243.88319.870510265.76322.747110289.87322.9953
#Mann= 3 , 0 , 0
9530.601    0.04       09530.601    0.04       010289.87    0.04       0
#XS Ineff= 2 , 0
       0                               0
Bank Sta=9530.601,10289.87
Exp/Cntr=0.3,0.1

Type RM Length L Ch R = 1 ,7849.453,148.685500,148.685500,148.685500
XS GIS Cut Line= 6
783286.261713843801569.412469326 783434.50016607801399.037762822
783494.902966484 801286.94006983783499.869811246801231.163877666
783458.811743977801082.726815292783494.924203667800926.163555506
#Sta/Elev= 30
9529.549311.45429548.927 305.0279562.372303.53039575.817 305.4359602.708315.1929
9647.341318.50969677.853314.47699695.735317.68789724.869 314.8229734.698312.8536
9774.049300.04099791.783296.27389831.196291.03559895.689291.59539935.927295.0658
9966.552294.9935  9977.4288.16659988.399285.2885   10001286.385610021.63290.6898
10042.52287.023910052.89287.5001 10103.1307.848710113.11314.579410123.13318.0508
 10194.6 318.49310204.99319.721410226.17318.846510236.87321.545510257.04321.5624
#Mann= 3 , 0 , 0
9529.549  0.0516       09529.549  0.0516       010257.04  0.0516       0
#XS Ineff= 2 , 0
       0                               0
Bank Sta=9529.549,10257.04
Exp/Cntr=0.3,0.1

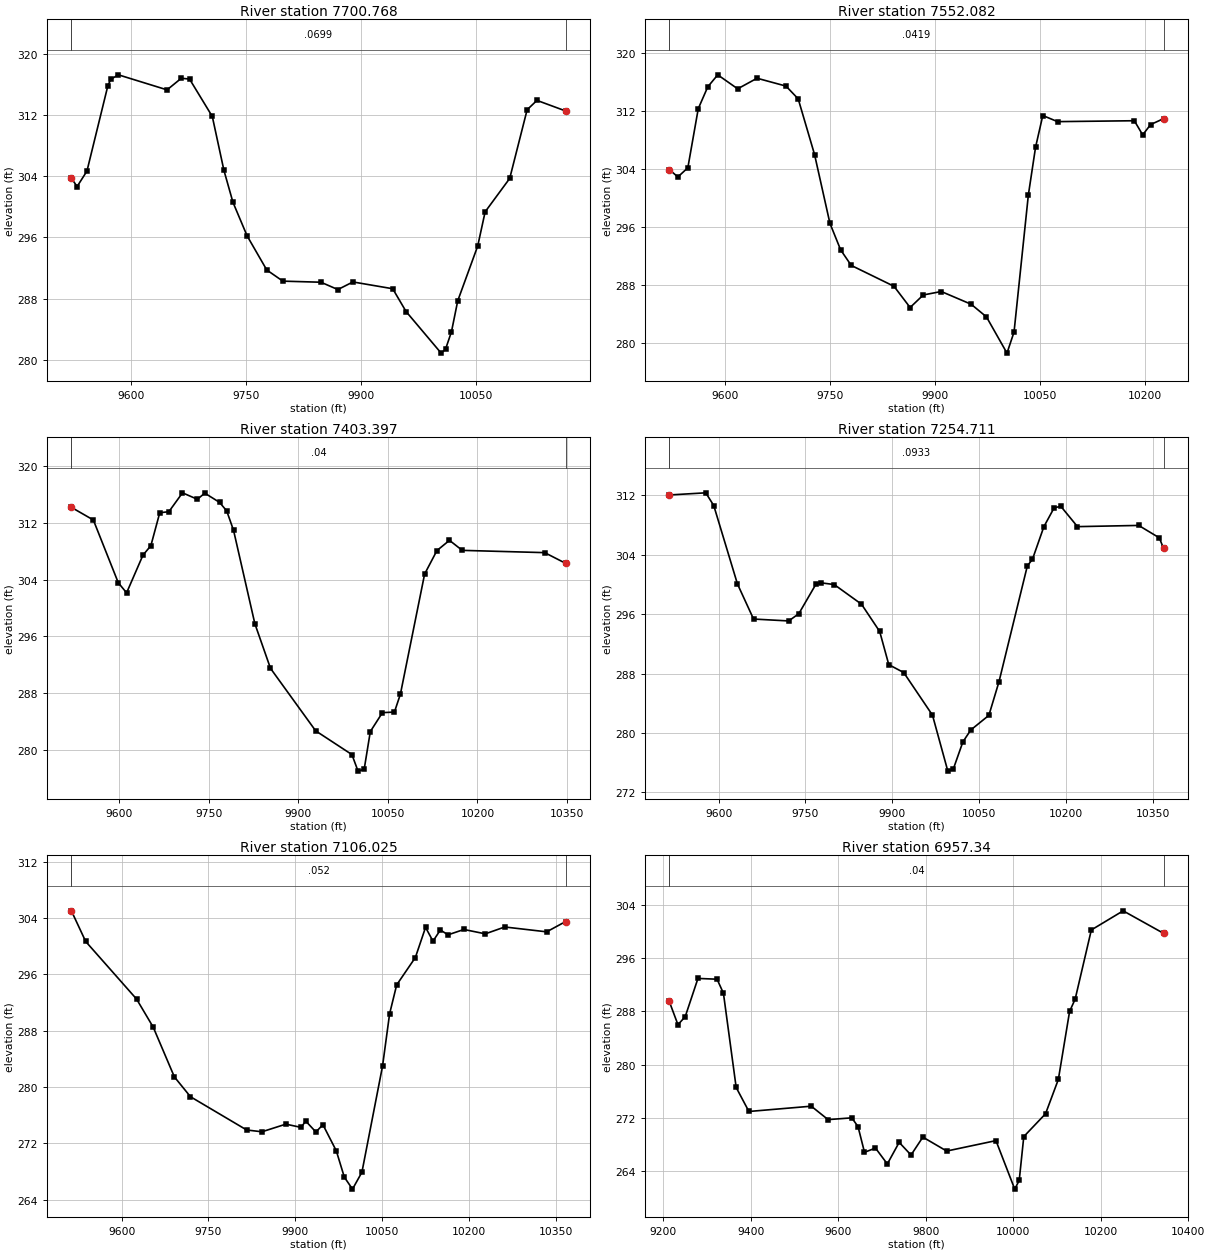
Type RM Length L Ch R = 1 ,7700.768,148.685600,148.685600,148.685600
XS GIS Cut Line= 6
783309.905828108801559.839916377 783481.90473463801371.877183888
783522.600289293801316.914566296783582.362104757801220.689201289
783654.984308159801147.829873136783720.495660963801065.738702296
#Sta/Elev= 30
9521.961303.7291 9529.43302.64239542.251304.65889569.597315.8364 9573.42316.6647
 9583.27317.23899646.737315.27469665.307316.79059676.063316.68599705.742311.7949
9720.884304.76219732.655 300.5869751.168296.18759776.766291.73829797.765290.2785
9847.379290.13769869.494289.17949889.123290.17349941.016289.28599958.494286.3002
10004.18280.8723 10009.9281.382310017.64283.666610025.81287.706110051.87294.8701
10061.55299.336910093.61303.705410116.32312.674910129.11313.899210166.55312.5147
#Mann= 3 , 0 , 0
9521.961  0.0699       09521.961  0.0699       010166.55  0.0699       0
#XS Ineff= 2 , 0
       0                               0
Bank Sta=9521.961,10166.55
Exp/Cntr=0.3,0.1

Type RM Length L Ch R = 1 ,7552.082,148.685500,148.685500,148.685500
XS GIS Cut Line= 6
783316.352054193801574.574949267783456.031138012801437.012121628
783544.838106157801366.058527723783637.562909081801319.435770225
783816.616105049  801270.6995182783910.861227202801219.697215097
#Sta/Elev= 30
9519.995303.92939532.323302.90589546.579 304.1749561.492 312.327 9575.09315.3337
9589.346316.99379617.858315.06299645.615316.52379687.032315.4392 9704.48313.6766
9727.885305.99919749.865296.5163 9765.22292.84439780.368290.70379841.545287.8235
9864.626284.89539883.447286.62539909.228287.10229951.988285.34359973.858 283.602
10003.23278.602310013.33 281.517 10033.8300.416510044.12307.010910054.45311.3828
10075.53310.537210185.45310.6606 10197.4308.709410208.75 310.13310227.23 310.946
#Mann= 3 , 0 , 0
9519.995  0.0419       09519.995  0.0419       010227.23  0.0419       0
#XS Ineff= 2 , 0
       09916.413                       0
Bank Sta=9519.995,10227.23
Exp/Cntr=0.3,0.1

Type RM Length L Ch R = 1 ,7403.397,148.685600,148.685600,148.685600
XS GIS Cut Line= 6
783288.582199033801656.446653018783513.618251906801470.394824826
783608.115937074801442.341635591783790.428227285801458.135650267
783892.281840717801423.545905262784013.549463713801347.662555995
#Sta/Elev= 30
9520.037314.16299556.815312.38449598.579303.5468  9612.5302.12869639.875307.4339
9653.117308.76669668.006313.40359683.261313.55029706.085316.20639731.008315.2979
9743.364316.16469768.074314.86569780.089313.66489791.613 310.9129827.203297.7966
9853.403291.50339929.071282.70499989.756279.36399999.992277.035910010.28277.3013
10020.55282.602310040.83285.266910060.92 285.34910070.95287.878710111.48304.7769
10132.09308.079210153.08309.519810174.48308.107710312.53307.787810347.61306.2817
#Mann= 3 , 0 , 0
9520.037    0.04       09520.037    0.04       010347.61    0.04       0
#XS Ineff= 2 , 0
       09945.054                       0
Bank Sta=9520.037,10347.61
Exp/Cntr=0.3,0.1

Type RM Length L Ch R = 1 ,7254.711,148.685500,148.685500,148.685500
XS GIS Cut Line= 6
783369.208938989801904.386481186783507.984973186801776.144697094
783692.197685085801624.392500834783768.917561678801541.998174398
 783966.22513343801417.731718949784030.844541181801369.214883305
#Sta/Elev= 30
9514.525312.03039577.653312.31849591.439310.60479632.395300.05379660.235295.3308
 9721.03295.07449738.504296.05089768.213300.04089777.372300.19959799.668299.9736
9846.851297.32829878.306293.65719894.034289.1917 9919.89 288.1289969.575282.3934
9996.117 274.86110005.59275.142510022.14278.7978 10035.8280.398910067.09282.3712
 10084.5286.878410133.61302.495210142.32303.352310162.16307.761410179.93310.3069
10191.51310.499110220.25307.768410326.09307.9304 10361.7306.262310369.02304.8487
#Mann= 3 , 0 , 0
9514.525  0.0933       09514.525  0.0933       010369.02  0.0933       0
#XS Ineff= 2 , 0
       0                               0
Bank Sta=9514.525,10369.02
Exp/Cntr=0.3,0.1

Type RM Length L Ch R = 1 ,7106.025,148.685600,148.685600,148.685600
XS GIS Cut Line= 6
783506.526953127802052.754948987783774.564390898801772.183159901
783811.482786469801721.941913078783844.665048819801655.726851644
783918.369423309801557.250713872784065.441957094801412.328586216
#Sta/Elev= 30
9513.119305.00489537.858300.65519625.808292.48469654.528288.50759691.129281.4477
9718.996278.63179816.084273.91519842.529273.66229883.817274.74379910.319 274.282
9918.054275.19089935.769273.63059947.876274.67169971.005270.95739984.896267.2237
    9999265.526810015.28267.923810050.92282.984610063.14290.397710075.35294.4977
10107.67298.383910125.27302.6573 10138.1300.701110150.94302.293910163.99301.5969
10191.59302.358610228.56301.740910262.17302.713610334.58302.025110367.42303.4857
#Mann= 3 , 0 , 0
9513.119   0.052       09513.119   0.052       010367.42   0.052       0
#XS Ineff= 2 , 0
       0                               0
Bank Sta=9513.119,10367.42
Exp/Cntr=0.3,0.1

Type RM Length L Ch R = 1 , 6957.34,148.685500,148.685500,148.685500
XS GIS Cut Line= 6
783399.950787544802299.438478936783875.601033208801790.653622985
 783921.90485149801754.814286529783998.526568001801729.071601661
784041.064242669801693.215803534784179.031540334801499.438802001
#Sta/Elev= 30
9213.364289.51539233.225286.01559249.845287.22379278.972292.97899322.663292.8606
9337.226290.74919366.353276.5621 9395.48272.94939538.066273.74569576.512271.7242
9630.693271.98999644.949270.67879659.774266.80319684.875267.44489711.965265.0455
9739.056268.30189766.147266.39289793.204269.08959847.676266.99119960.356 268.562
10003.28261.260110013.56262.575210023.99269.165710073.75272.607110103.05277.7767
10128.74288.015510141.46289.857110178.43300.275910251.19303.154610343.54299.7693
#Mann= 3 , 0 , 0
9213.364    0.04       09213.364    0.04       010343.54    0.04       0
#XS Ineff= 2 , 0
       09919.912                       0
Bank Sta=9213.364,10343.54
Exp/Cntr=0.3,0.1

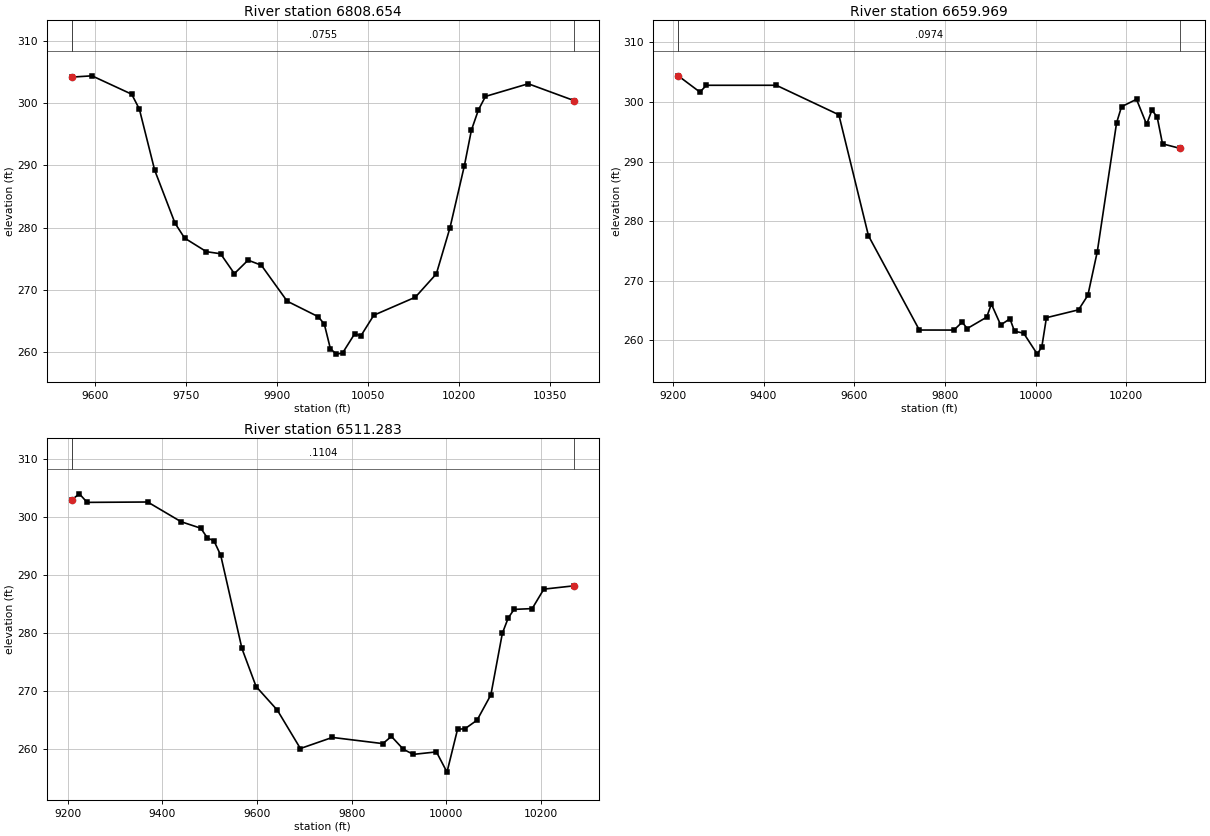
Type RM Length L Ch R = 1 ,6808.654,148.685600,148.685600,148.685600
XS GIS Cut Line= 6
783818.127310377802230.409948116 783914.31512758802113.144446228
783985.386474531801999.142349407784020.119888811801895.916823655
784031.390949311801798.840481051 784203.16744889801512.385266358
#Sta/Elev= 30
9561.117304.14019594.436 304.3469659.943301.39939672.577299.01249697.844289.2172
9731.389280.71039747.236278.32469783.127276.1488  9806.5275.81319829.269272.6259
9851.854274.78889873.739273.97429916.363268.20669967.551  265.729977.609 264.534
9987.634260.58019997.634259.718210007.64259.8884 10027.7262.984510037.86262.6412
10059.21 265.956 10127.7268.845310162.38272.592610184.86279.988410208.61289.9407
10220.17295.626910231.73298.877810243.39301.046110313.92303.074110389.12300.3872
#Mann= 3 , 0 , 0
9561.117  0.0755       09561.117  0.0755       010389.12  0.0755       0
#XS Ineff= 2 , 0
       0                               0
Bank Sta=9561.117,10389.12
Exp/Cntr=0.3,0.1

Type RM Length L Ch R = 1 ,6659.969,148.685500,148.685500,148.685500
XS GIS Cut Line= 6
 783727.83987648802479.009403279 783975.05129513802224.715874247
784096.036917714802070.540245458784154.594901081801953.398073189
784195.954646828801710.726506543784274.780420977801550.798354829
#Sta/Elev= 30
9211.796304.38029259.714301.64749273.804302.79219428.108302.79589566.089297.8445
9631.421277.53959743.676261.71989819.889261.71199838.202263.04399849.251261.9671
9892.226263.87899902.546266.08329923.058262.56729943.496263.60729953.559261.5199
9973.683261.194610003.86257.674210013.92258.926710023.97263.788810094.82265.1092
10115.36267.546410136.16274.860810178.76296.493810189.62299.1984 10222.7300.4423
10245.01296.227710256.59298.614410268.16297.503510280.04292.967710319.32292.1932
#Mann= 3 , 0 , 0
9211.796  0.0974       09211.796  0.0974       010319.32  0.0974       0
#XS Ineff= 2 , 0
       09790.785                       0
Bank Sta=9211.796,10319.32
Exp/Cntr=0.3,0.1

Type RM Length L Ch R = 1 ,6511.283,148.685600,148.685600,148.685600
XS GIS Cut Line= 6
  783783.6189554802457.868671275783996.159813752 802244.31633416
784208.286634717801995.028264768784295.879161909801911.680849542
784373.289460788801781.041596842784469.739594484801655.374156695
#Sta/Elev= 30
9208.848302.90759224.875303.94199241.328302.47129369.155302.53519439.556299.1507
9481.344298.02419495.273296.35439509.203295.84089523.364293.37959568.188277.3417
9598.071270.79999642.908266.74119691.605260.1391 9759.06262.04749865.719260.9823
9883.795262.22449909.175259.9993  9930.2259.13319978.873259.556910001.22 256.079
10023.51263.452110039.18263.5378 10064.7265.017510093.86269.368110118.11279.9603
 10130.5282.588610142.88284.0654 10181.1284.203710205.69287.548910269.08288.1191
#Mann= 3 , 0 , 0
9208.848  0.1104       09208.848  0.1104       010269.08  0.1104       0
#XS Ineff= 2 , 0
       09722.999                       0
Bank Sta=9208.848,10269.08
Exp/Cntr=0.3,0.1