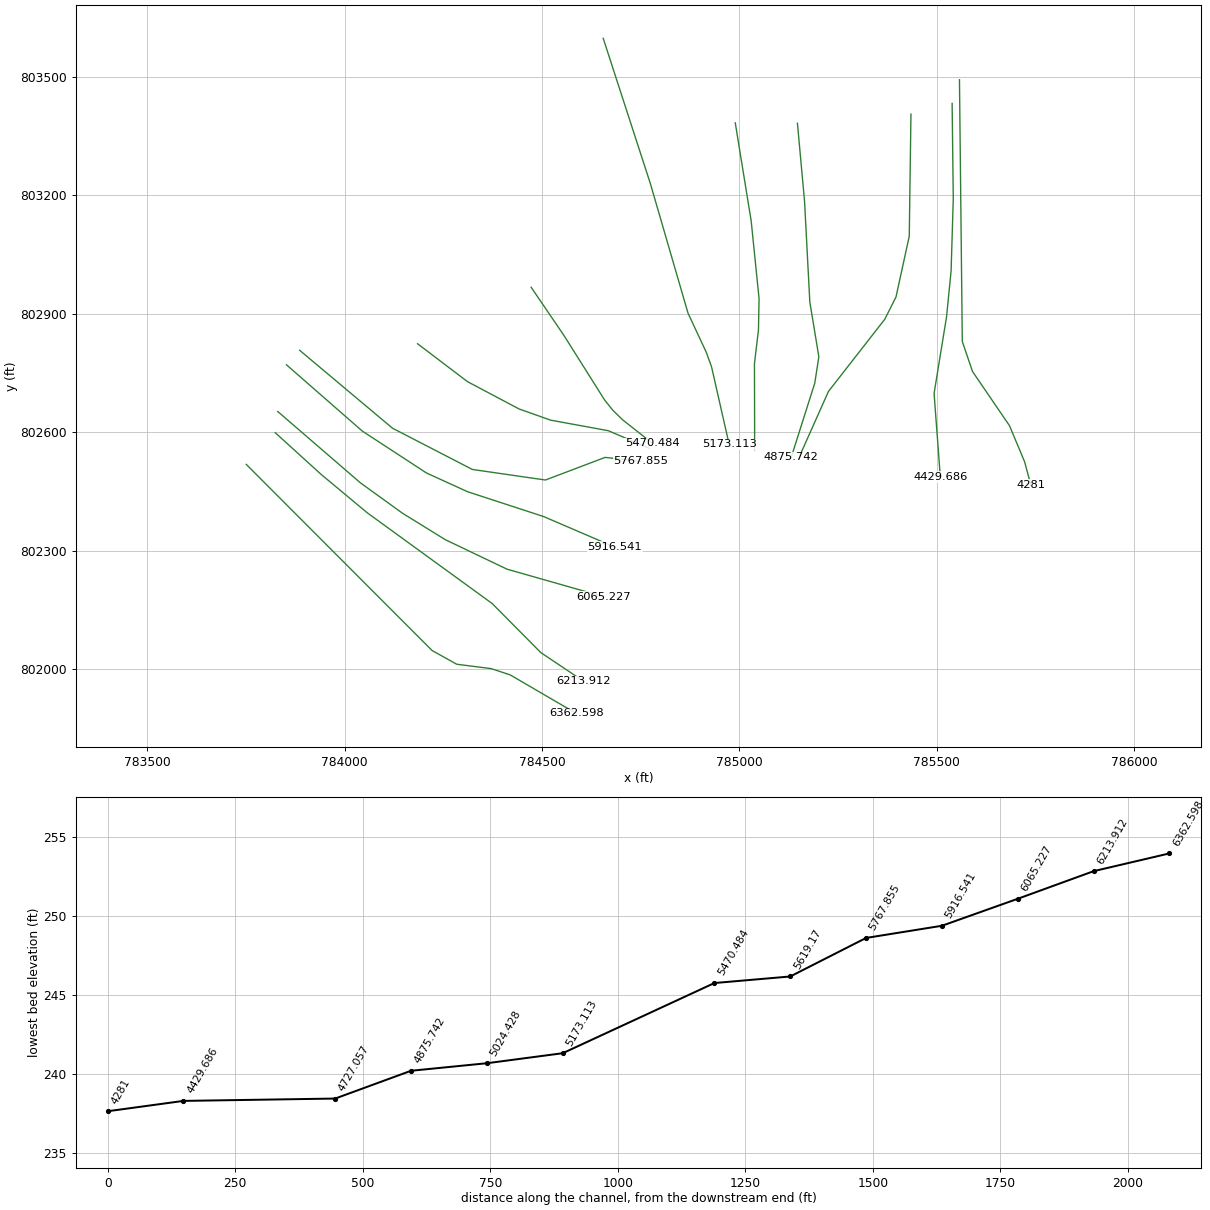
HEC-RAS study 17671_ras.prj: 17671

--- 17671_ras.g01 (geometry) --- (continued)

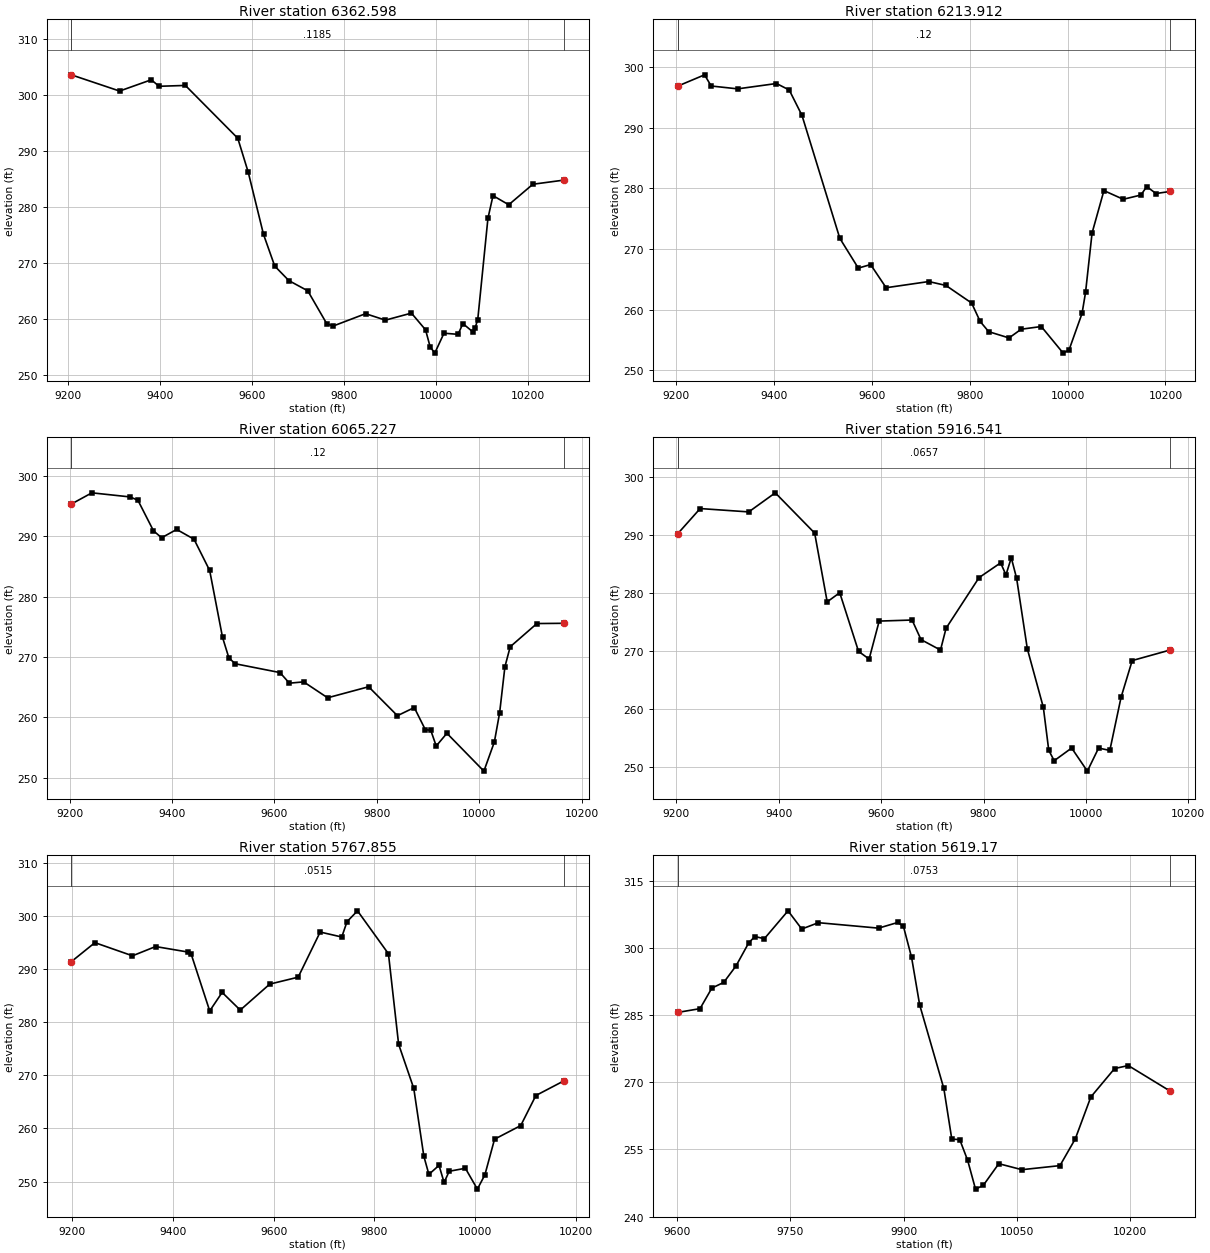
Type RM Length L Ch R = 1 ,6362.598,148.685500,148.685500,148.685500
XS GIS Cut Line= 6
783750.748760611802518.415951416784221.469738391802046.979399176
784283.945587451802012.235259514784371.311522883802001.086985494
784419.370985586801985.236451704784586.465149996801887.775444379
#Sta/Elev= 30
9207.961 303.6279312.933300.73099381.802302.74329398.722301.58069455.915301.7328
9569.823292.29979592.647286.20119625.738 275.1349650.123 269.4789680.806266.8877
9721.897265.06219762.987259.21779776.684258.7584 9847.58260.97789890.635259.8235
9947.218261.07949977.919258.10069987.953255.05259997.971253.934410018.02257.4915
10048.62 257.28910059.09259.213810080.48257.7421 10085.7258.456910091.38259.9157
10113.52 278.00210124.58282.050510158.75280.429210211.24284.089510278.87284.8309
#Mann= 3 , 0 , 0
9207.961  0.1185       09207.961  0.1185       010278.87  0.1185       0
#XS Ineff= 2 , 0
       09780.783                       0
Bank Sta=9207.961,10278.87
Exp/Cntr=0.3,0.1

Type RM Length L Ch R = 1 ,6213.912,148.685600,148.685600,148.685600
XS GIS Cut Line= 6
783824.173038666802598.713764854783940.201114607802493.279953169
784057.011997988802396.014618987784373.564204799802166.090850938
784497.118097749802041.506698824784605.287959688801969.189765809
#Sta/Elev= 30
 9203.66296.85559258.825298.73249272.337296.88949326.384296.41729405.719297.2992
9431.745296.22769457.771292.03729535.056  271.759572.774266.83879597.919267.4249
9629.603263.60229716.704264.62319751.683263.97849804.152261.07719821.642258.0311
9839.025256.35299880.535255.31739905.375256.75589946.434257.19999991.132252.8111
 10003.1253.336310029.63259.355110036.77262.8175 10050.1272.625510074.32279.6299
10113.75278.196210149.85278.898810161.76280.293810180.63279.144510209.74279.4912
#Mann= 3 , 0 , 0
 9203.66    0.12       0 9203.66    0.12       010209.74    0.12       0
#XS Ineff= 2 , 0
       0                               0
Bank Sta=9203.66,10209.74
Exp/Cntr=0.3,0.1

Type RM Length L Ch R = 1 ,6065.227,148.685500,148.685500,148.685500
XS GIS Cut Line= 6
 783830.52822296802652.406637894 784039.75140325802471.816664745
784146.679292954802394.619223852784255.323601905802327.515676646
784411.343658183802253.014992059784654.873724772802183.663135245
#Sta/Elev= 30
9202.974295.3452 9243.21297.20919318.025296.52789333.142295.97389363.532 290.916
9379.372289.7574 9408.86 291.1389442.734289.51799473.331284.33599498.486273.2367
9510.965269.81499523.444268.86539610.692 267.4069629.061265.64749657.006 265.865
 9703.79263.22549783.914265.05529840.161260.25539873.108261.60699894.593257.9536
9905.336 257.8349915.972 255.2359936.873257.339510009.14251.065610029.59255.8989
10039.87260.7324 10050.2268.366710060.53 271.68210112.69275.535610165.66275.5753
#Mann= 3 , 0 , 0
9202.974    0.12       09202.974    0.12       010165.66    0.12       0
#XS Ineff= 2 , 0
       0                               0
Bank Sta=9202.974,10165.66
Exp/Cntr=0.3,0.1

Type RM Length L Ch R = 1 ,5916.541,148.685600,148.685600,148.685600
XS GIS Cut Line= 6
783852.603680565802770.745953999 784044.77358305 802602.75058962
784207.375833311802496.591931472784311.484210397802449.174434303
784503.781031651802386.364304993784683.862820354802309.049705282
#Sta/Elev= 30
9202.218290.22219246.422294.59689341.344294.01949393.135297.30659470.102290.3691
9494.591278.5242 9519.08280.09719555.813269.99079576.497268.66929596.136275.2094
9660.452275.39029677.829272.01919715.943270.21929726.795 273.9689791.265 282.698
 9833.38285.24199843.813283.16629854.247286.11249864.681282.56639885.548270.4395
9916.849260.34349927.426252.94929938.083251.15319972.143253.338210002.85249.3582
 10024.8 253.33410046.74252.925210068.69262.076210090.46268.407310164.77270.2291
#Mann= 3 , 0 , 0
9202.218  0.0657       09202.218  0.0657       010164.77  0.0657       0
#XS Ineff= 2 , 0
       0                               0
Bank Sta=9202.218,10164.77
Exp/Cntr=0.3,0.1

Type RM Length L Ch R = 1 ,5767.855,148.685500,148.685500,148.685500
XS GIS Cut Line= 6
783886.097453129802807.361278153784121.247450876 802610.04444502
784323.482553933 802505.59751508784508.548614396802478.856558628
784659.646873649802536.136554452784749.566240901802526.341759087
#Sta/Elev= 30
9198.093291.36399244.944294.94489319.616292.46979365.503294.21039429.138293.1902
9435.944292.8576    9473282.10589497.703285.58549533.644282.26039592.185287.1451
 9648.68288.45229692.393296.94019735.279296.00529745.694298.88539766.523300.9297
9827.998  292.85 9848.18275.84229878.285267.53259898.314254.76829908.319251.3594
9928.405253.0564 9938.53249.84429948.654251.94679980.794252.512210004.59248.5884
10019.53251.276510038.72257.977610090.75260.542110120.81266.195810176.67268.9613
#Mann= 3 , 0 , 0
9198.093  0.0515       09198.093  0.0515       010176.67  0.0515       0
#XS Ineff= 2 , 0
       0                               0
Bank Sta=9198.093,10176.67
Exp/Cntr=0.3,0.1

Type RM Length L Ch R = 1 , 5619.17,148.685600,148.685600,148.685600
XS GIS Cut Line= 6
784184.698428656802823.994862141784311.150462819802728.029314432
784441.798500533802658.804538154784521.697841313802630.521900235
784668.010279101802603.699202445784771.146578159802559.465067443
#Sta/Elev= 30
9600.263285.58079630.075286.4293 9645.77291.02069661.532292.29149677.855 295.981
9694.807 301.161 9702.88302.52779715.339302.03729746.756308.26069764.955304.2003
9787.014305.61269866.782304.39539892.119305.65759899.703304.83689910.584297.8496
 9921.27287.27269953.326268.6103  9963.9257.29739974.405257.21219984.909252.5734
 9995.33246.151710005.57 246.977 10026.2251.828110056.81250.489910107.29251.3983
 10127.6257.365610148.21266.713710179.73273.062910197.87273.7305 10253.5268.0148
#Mann= 3 , 0 , 0
9600.263  0.0753       09600.263  0.0753       0 10253.5  0.0753       0
#XS Ineff= 2 , 0
       0                               0
Bank Sta=9600.263,10253.5
Exp/Cntr=0.3,0.1

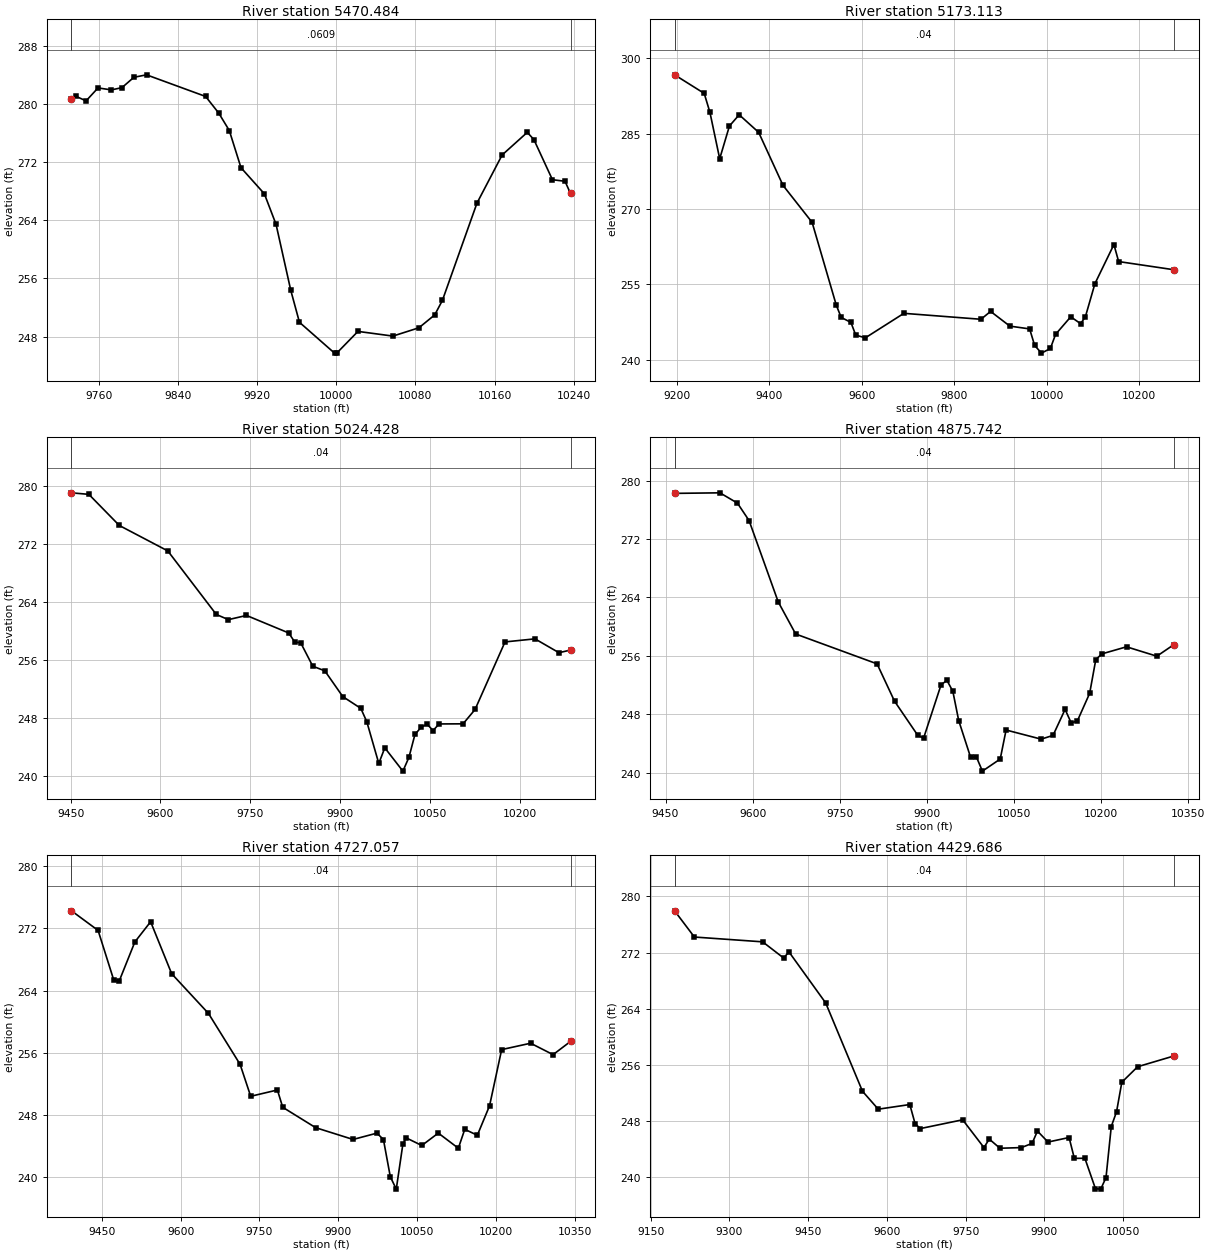
Type RM Length L Ch R = 1 ,5470.484,297.371100,297.371100,297.371100
XS GIS Cut Line= 6
784472.322777782802967.195069985784556.102389845802844.015680355
784658.252321564802681.824655983784679.092664438  802655.8495006
784703.876794605802631.452340221784779.370665452 802572.08808515
#Sta/Elev= 30
9732.088280.70729736.849281.00839746.837280.39029758.931282.17569772.411281.9022
9783.118282.21239795.212283.63449807.974283.97319867.775281.00139881.059  278.71
9891.721276.32149903.547271.2105  9927.2267.62349939.026263.4221 9953.92254.3557
9962.679249.97419998.158245.7366   10001 245.82110021.87248.721710057.22248.0778
10083.53249.218910099.51250.987610107.26252.972810142.26266.3485 10167.7272.9594
10193.14276.0694 10199.8275.084510218.59269.560710231.31269.348610236.87267.6699
#Mann= 3 , 0 , 0
9732.088  0.0609       09732.088  0.0609       010236.87  0.0609       0
#XS Ineff= 2 , 0
       0                               0
Bank Sta=9732.088,10236.87
Exp/Cntr=0.3,0.1

Type RM Length L Ch R = 1 ,5173.113,148.685500,148.685500,148.685500
XS GIS Cut Line= 6
784654.907367566803597.609214947784774.310393724 803229.78489869
784869.750461059802901.449800201784916.222459512802801.801508208
784929.271787276802765.815470221784973.955856492 802568.88363147
#Sta/Elev= 30
9195.682296.69799259.742293.0041 9272.15289.20929293.213279.99369314.276286.5139
9335.339288.74739377.465285.24929430.122274.6927 9493.05 267.3319545.482250.7978
9555.968248.40339576.941247.41479587.393244.8838 9608.22244.34569691.532249.2209
9858.154248.03729878.982249.60539920.638246.67369963.419246.12149974.287242.8179
9989.059241.298810008.25242.225310019.56 245.04410052.34248.534710073.59247.1608
10083.93248.5201 10104.6255.126910145.65262.918410155.88259.525910274.72257.9058
#Mann= 3 , 0 , 0
9195.682    0.04       09195.682    0.04       010274.72    0.04       0
#XS Ineff= 2 , 0
       09905.745                       0
Bank Sta=9195.682,10274.72
Exp/Cntr=0.3,0.1

Type RM Length L Ch R = 1 ,5024.428,148.685600,148.685600,148.685600
XS GIS Cut Line= 6
784989.399891566803383.499597348785029.772875274803134.608210424
785049.675627687802938.086736953785048.151606813802859.262894821
785038.012503854802773.709056899   785038.531133802555.781401452
#Sta/Elev= 30
9451.463279.06069480.433278.84939531.258274.5581  9612.2271.04599693.121262.2798
9713.303261.56489743.501262.14419813.963259.72679824.029258.48449834.095258.3555
9854.168255.13779874.218254.50329904.286250.94469934.287249.32569944.288247.4895
9964.321241.72379974.345243.877510004.55240.664810014.62242.562810024.69245.7287
10034.75246.693910044.82247.154410054.88246.265310064.95247.174210104.97  247.19
10124.98249.168410174.99258.4913   10225258.913910265.01257.003710284.28257.3662
#Mann= 3 , 0 , 0
9451.463    0.04       09451.463    0.04       010284.28    0.04       0
#XS Ineff= 2 , 0
       0                               0
Bank Sta=9451.463,10284.28
Exp/Cntr=0.3,0.1

Type RM Length L Ch R = 1 ,4875.742,148.685500,148.685500,148.685500
XS GIS Cut Line= 6
785146.836421614803382.629782261785164.885942304803184.780842638
785178.258196548802929.764791665785201.089351924802791.221634585
785190.818404347802724.387300635785131.328048553802536.953041771
#Sta/Elev= 30
9465.627278.27539543.733278.35049573.827276.94039593.889274.54599644.041263.4002
9674.113258.9904 9814.26254.89899844.292249.78529884.377245.09479894.403244.7154
9924.519252.0376 9934.62252.62729944.721 251.1429954.822247.12979975.187242.1158
9985.422242.11179995.657240.188410026.34241.848110036.42 245.82710096.78244.5743
10117.24245.086510138.03248.6516 10148.6246.788910159.18247.077310180.33 250.857
10190.91255.490110201.49256.2692 10243.8257.2363   10296255.948910324.87257.5089
#Mann= 3 , 0 , 0
9465.627    0.04       09465.627    0.04       010324.87    0.04       0
#XS Ineff= 2 , 0
       0                               0
Bank Sta=9465.627,10324.87
Exp/Cntr=0.3,0.1

Type RM Length L Ch R = 1 ,4727.057,297.371100,297.371100,297.371100
XS GIS Cut Line= 6
785434.409827411803405.614479151785430.120211365803096.425452544
 785396.52492942 802942.45433652785368.019547193802885.916793892
785225.533876362802703.421424709785149.635917131802533.238401769
#Sta/Elev= 30
9392.141274.26379442.783271.74019472.784 265.3079482.785265.19519512.787270.2597
9542.788272.85769582.796266.1669 9652.88261.05199713.084254.4922 9733.24250.3845
 9784.05251.1966 9794.24248.96819856.923246.34329928.118 244.827 9973.54245.6408
9985.897 244.817    9999240.023210010.33238.431410022.99244.262810029.38245.0249
10058.96 244.05110090.34245.647110128.48243.6973 10140.7 246.13110164.65245.3664
 10187.9249.164410210.92256.396310266.07257.216810308.82255.747210341.98257.4459
#Mann= 3 , 0 , 0
9392.141    0.04       09392.141    0.04       010341.98    0.04       0
#XS Ineff= 2 , 0
       0                               0
Bank Sta=9392.141,10341.98
Exp/Cntr=0.3,0.1

Type RM Length L Ch R = 1 ,4429.686,148.685600,148.685600,148.685600
XS GIS Cut Line= 6
785538.691303185803432.687859163785541.609580093803190.847263778
785536.101183448803008.858132362785524.654000452802892.918614064
785492.982988598802698.081594972785508.803253698802486.645270548
#Sta/Elev= 30
9195.685277.95649233.376274.22079363.385273.53519403.388271.22589413.389272.1088
9483.396264.82339553.429252.23629583.458249.6787 9643.57250.34149653.603 247.615
9663.636 246.9169744.183248.16759784.723244.20829794.857245.41639815.215244.1095
9856.008244.20549876.404244.80279886.569246.55669906.753244.99359946.842245.6422
9956.852242.66519976.896242.68269997.003238.351910007.07238.282910017.12239.9235
10027.16247.205310037.21 249.31410047.26253.521310077.38 255.73310145.84257.2524
#Mann= 3 , 0 , 0
9195.685    0.04       09195.685    0.04       010145.84    0.04       0
#XS Ineff= 2 , 0
       0                               0
Bank Sta=9195.685,10145.84
Exp/Cntr=0.3,0.1

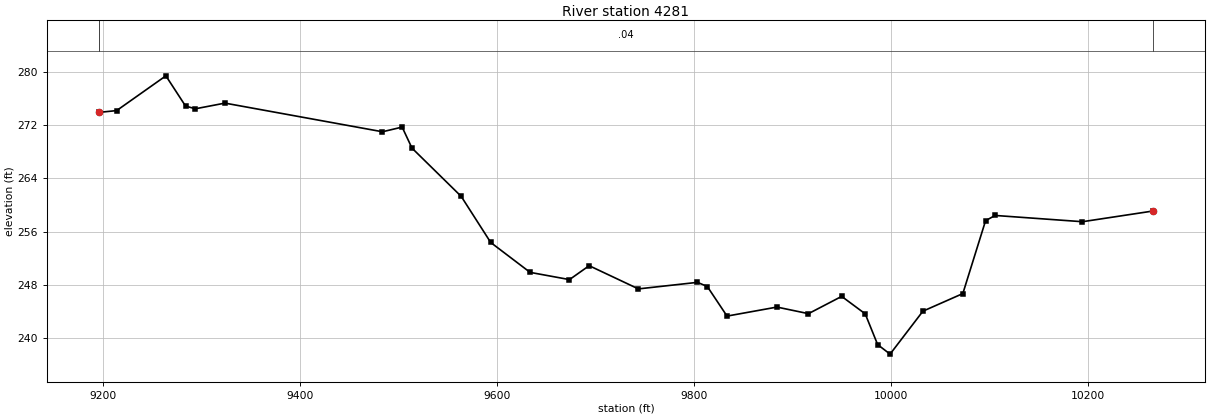
Type RM Length L Ch R = 1 ,    4281,0.000000,0.000000,0.000000
XS GIS Cut Line= 6
 785557.28793585803492.719882822785564.461691219802829.566236558
785590.365443972802753.717673116785683.939154247802616.588334613
785722.252018385802525.136807486 785738.10996069802466.391050381
#Sta/Elev= 30
9195.728273.8927 9213.45274.15989263.456279.37369283.459 274.833 9293.46274.4316
9323.464275.27999483.485270.98349503.487271.68439513.488268.5307 9563.49261.2913
9593.492254.37369633.494249.89169673.496248.80879693.497250.8948  9743.5247.4137
9803.516248.39589813.523247.77129833.557243.33419884.278244.68739916.288243.6991
 9950.04246.2907 9973.95243.67169986.575  239.069999.202237.629310032.57244.0718
10073.13246.712610096.23257.646110105.94258.430410194.66257.491410266.06259.0889
#Mann= 3 , 0 , 0
9195.728    0.04       09195.728    0.04       010266.06    0.04       0
#XS Ineff= 2 , 0
       0                               0
Bank Sta=9195.728,10266.06
Exp/Cntr=0.3,0.1